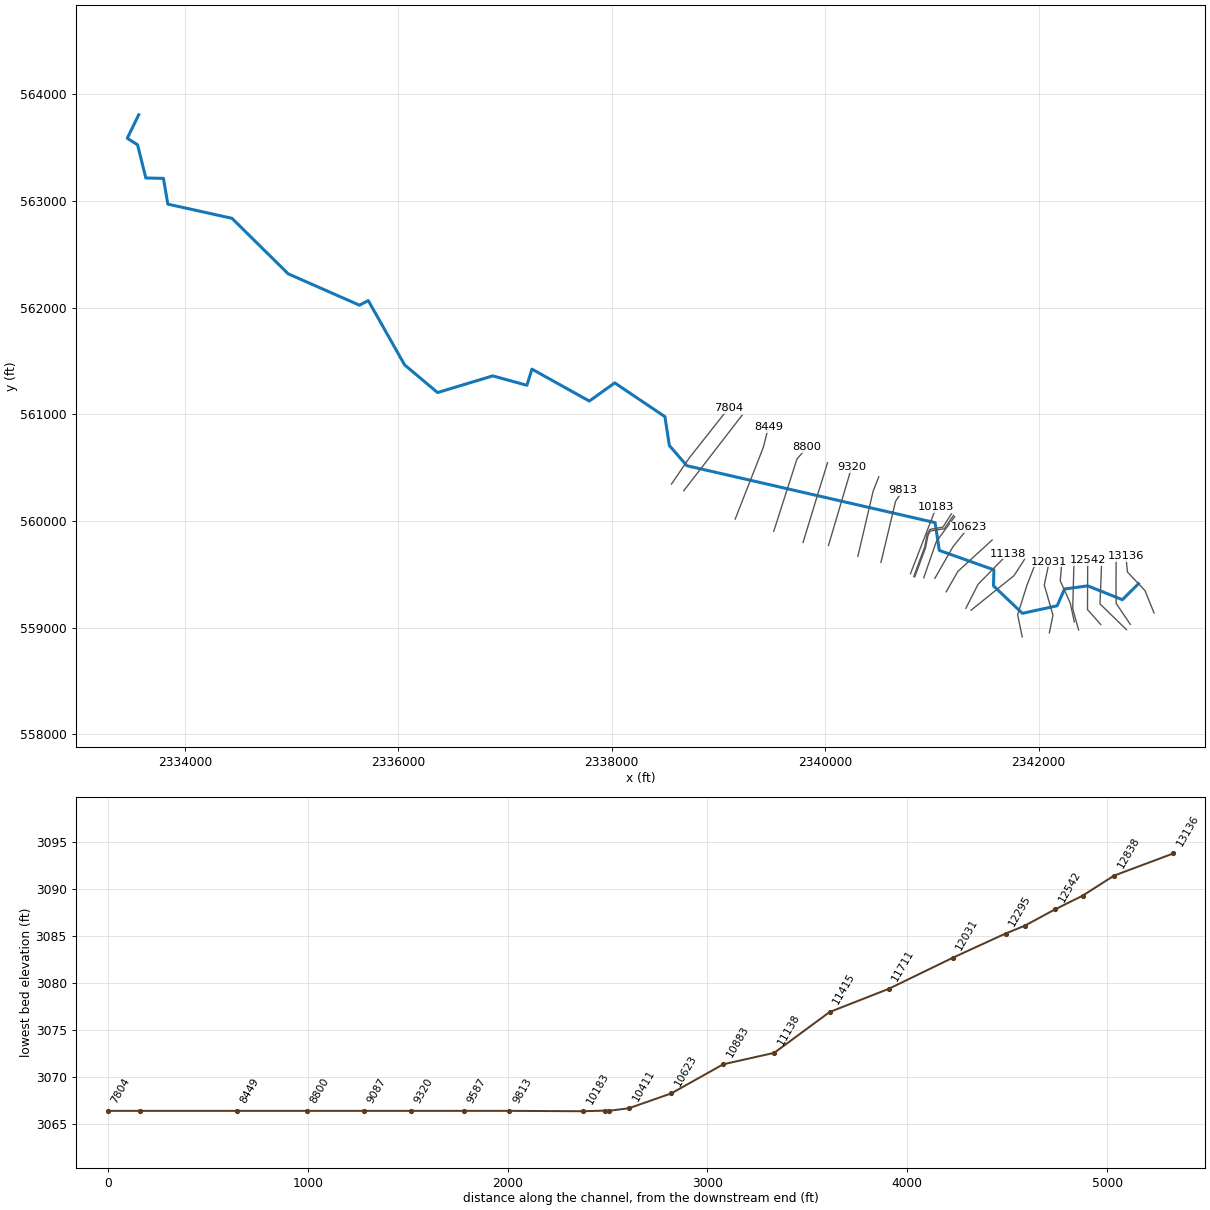
--- BFLFK.prj (project) ---

Proj Title=BFLFK
Current Plan=p01
Default Exp/Contr=0,0
English Units
Geom File=g01
Flow File=f01
Plan File=p01
Background Map Layer=Inundation Boundary (01pct Value_0)
BEGIN DESCRIPTION:
----------MODEL BY WOOD PLC 2021----------
Stream Name: Buffalo Fork
Flood Zone: Enhanced Approximate
Pocahontas County, WV
HEC-RAS Version: RAS 6.1
Vertical Datum: NAVD88
Projection: NAD 1983 StatePlane West Virginia S FIPS 4702 (US Feet)
Terrain: 1-meter LIDAR (FEMA Region III 3DEP collected 2016-2018)
Land Use: 2019 NLCD
Hydrologic Method:
WV SIR2010-5033 regression equations
Model Notes:
coincident peak / KWSEL tie in with LTTLRV2- WSEL's updated from XS 7750
END DESCRIPTION:
DSS Export Rating Curves= 0
DSS Export Rating Curve Sorted= 0
DSS Export Volume Flow Curves= 0
DXF OffsetX= 0
DXF OffsetY= 0
DXF ScaleX= 0
DXF ScaleY= 0

--- BFLFK.p01 (plan) ---

Plan Title=Floodplain
Program Version=6.10
Short Identifier=Floodplain
Geom File=g01
Flow File=f01
Subcritical Flow
K Sum by GR= 0
Std Step Tol= 0.01
Critical Tol= 0.01
Num of Std Step Trials= 20
Max Error Tol= 0.3
Flow Tol Ratio= 0.001
Split Flow NTrial= 30
Split Flow Tol= 0.02
Split Flow Ratio= 0.02
Log Output Level= 0
Friction Slope Method= 1
Unsteady Friction Slope Method= 2
Unsteady Bridges Friction Slope Method= 1
Parabolic Critical Depth
Global Vel Dist= 0 , 0 , 0
Global Log Level= 0
CheckData=True
Encroach Param=-1 ,0,0, 0
Mapping Interval=1HOUR
Computation Time Step Use Courant=        0
Computation Time Step Use Time Series=    0
Computation Time Step Count To Double=0
Computation Time Step Max Doubling=0
Computation Time Step Max Halving=0
Computation Time Step Residence Courant=0
Run HTab= 0
Run UNet= 0
Run Sediment= 0
Run PostProcess= 0
Run WQNet= 0
Run RASMapper=-1
UNET Theta= 0
UNET Theta Warmup= 0
UNET ZTol= 0
UNET ZSATol= 0
UNET MxIter= 0
UNET Max Iter WO Improvement= 0
UNET MaxInSteps= 0
UNET DtIC= 0
UNET DtMin= 0
UNET MaxCRTS= 0
UNET WFStab= 0
UNET SFStab= 0
UNET WFX= 1
UNET SFX= 1
UNET Gravity=32.174
UNET 1D Methodology=Finite Difference
UNET DSS MLevel= 1
UNET Pardiso=0
UNET DZMax Abort= 0
UNET Use Existing IB Tables= 0
UNET Froude Reduction=False
UNET Froude Limit= 0
UNET Froude Power= 0
UNET D1 Cores= 0
UNET WindReference=Eulerian
UNET WindDragFormulation=Hsu (1988)
UNET D2 Coriolis=0
UNET D2 Cores= 0
UNET D2 Theta= 1
UNET D2 Theta Warmup= 1
UNET D2 Z Tol= 0.01
UNET D2 Volume Tol= 0.01
UNET D2 Max Iterations= 20
UNET D2 Equation= 0
UNET D2 RampUpFraction=0.1
UNET D2 TimeSlices= 1
UNET D2 Turbulence Formulation=Non-Conservative (original)
UNET D2 Eddy Viscosity=0.3
UNET D2 Transverse Eddy Viscosity=0.1
UNET D2 Smagorinsky Mixing=0
UNET D2 BCVolumeCheck=0
UNET D2 Cores=0
UNET D2 SolverType=PARDISO (Direct)
UNET D2 Minimum Iterations= 2147483647
UNET D2 Maximum Iterations= 2147483647
UNET D2 Restart Number= 10
UNET D2 Relaxation Coeff=1.3
UNET D2 SOR Precondition Iterations= 10
UNET D2 ILUT Maximum Fill= 8
UNET D2 ILUT Tolerance=1E-08
UNET D1D2 MaxIter= 0
UNET D1D2 ZTol=0.01
UNET D1D2 QTol=0.1
UNET D1D2 MinQTol=1
Write IC File= 0
Write IC File at Fixed DateTime=0
Write IC File at Sim End=0
Echo Input=False
Echo Parameters=False
Echo Output=False
Write Detailed= 0
HDF Write Warmup=0
HDF Write Time Slices=0
HDF Flush=0
HDF Compression= 1
HDF Chunk Size= 1
HDF Spatial Parts= 1
HDF Use Max Rows=0
HDF Fixed Rows= 1
Calibration Method= 0
Calibration Iterations= 20
Calibration Max Change=0.05
Calibration Tolerance=0.2
Calibration Maximum=1.5
Calibration Minimum=0.5
Calibration Optimization Method= 1
WQ AD Non Conservative
WQ ULTIMATE=-1
WQ Max Comp Step=1HOUR
WQ Output Interval=15MIN
WQ Output Selected Increments= 0
WQ Output face flow=0
WQ Output face velocity=0
WQ Output face area=0
WQ Output face dispersion=0
WQ Output cell volume=0
WQ Output cell surface area=0
WQ Output cell continuity=0
WQ Output cumulative cell continuity=0
WQ Output face conc=0
WQ Output face dconc_dx=0
WQ Output face courant=0
WQ Output face peclet=0
WQ Output face adv mass=0
WQ Output face disp mass=0
WQ Output cell mass=0
WQ Output cell source sink temp=0
WQ Output nsm pathways=0
WQ Output nsm derived pathways=0
WQ Create Restart=0
WQ Fixed Restart=0
WQ System Summary=0
WQ Write To DSS=0
Sorting and Armoring Iterations= 10
XS Update Threshold= 0.02
Bed Roughness Predictor= 0
Hydraulics Update Threshold= 0.02
Energy Slope Method= 1
Volume Change Method= 1
Sediment Retention Method= 0
Sediment TS Multiplier= 1
Warm Up Method= 0
XS Weighting Method= 0
Number of US Weighted Cross Sections= 1
Number of DS Weighted Cross Sections= 1
Upstream XS Weight=0
Main XS Weight=1
Downstream XS Weight=0
Number of DS XS's Weighted with US Boundary= 1
Upstream Boundary Weight= 1
Weight of XSs Associated with US Boundary= 0
Number of US XS's Weighted with DS Boundary= 1
Downstream Boundary Weight= 0.5
Weight of XSs Associated with DS Boundary= 0.5
Percentile Method= 0
Sediment Output Level= 3
Mass or Volume Output= 0
Output Increment Type= 1
Profile and TS Output Increment= 1
Transport Output Increment 1
XS Output Flag= 0
XS Output Increment= 10
Read HDF5 Sediment Hotstart= 0
Sediment Hotstart Type= 0
Write Gradation File= 0
Read Gradation Hotstart= 0
Write HDF5 File= 1
Write Binary Output= 1
Write DSS Sediment File= 0
DSS Sediment Output Type= 1
SV Curve= 0
Specific Gage Flag= 0
Subcell Erosion Methods= 0
Subcell Deposition Methods= 0
Advection Scheme= 1
Matrix Solver= 0
Implicit Weighting Factor= 1
Maximum Outer Loop Convergence Iterations= 5
Convergence Maximum Absolute= 0.001
Convergence RMSE= 0.0001
Grain Fractions Max Abs Error= 0.001
Max Subgrid Regions= 1
Max Subgrid Length Scale= 3.402823E+38
Initial Layer Thickness= 3.402823E+38
Min Layer Thickness= 3.402823E+38
Max Layer Thickness= 3.402823E+38
Number of Layers= 5

--- BFLFK.f01 (steady flow) ---

Flow Title=Flow
Program Version=6.10
Number of Profiles= 6
Profile Names=01pct,10pct,04pct,02pct,0_2pct,01plus
River Rch & RM=BFLFK,Main            ,13136
    1010     546     718     859    1400    1490
River Rch & RM=BFLFK,Main            ,9087
    1130     611     803     960    1550    1670
River Rch & RM=BFLFK,Main            ,4880
    1330     724     948    1130    1820    1960
River Rch & RM=BFLFK,Main            ,0
    2840    1600    2060    2440    3850    4200
Boundary for River Rch & Prof#=BFLFK,Main            , 1
Up Type= 0
Dn Type= 1
Dn Known WS=2939.6
Boundary for River Rch & Prof#=BFLFK,Main            , 2
Up Type= 0
Dn Type= 1
Dn Known WS=2938.7
Boundary for River Rch & Prof#=BFLFK,Main            , 3
Up Type= 0
Dn Type= 1
Dn Known WS=2939
Boundary for River Rch & Prof#=BFLFK,Main            , 4
Up Type= 0
Dn Type= 1
Dn Known WS=2939.4
Boundary for River Rch & Prof#=BFLFK,Main            , 5
Up Type= 0
Dn Type= 1
Dn Known WS=2940
Boundary for River Rch & Prof#=BFLFK,Main            , 6
Up Type= 0
Dn Type= 1
Dn Known WS=2940.1
DSS Import GetInterval= 0
DSS Import GetPeak= 0
DSS Import FillOption= 0

--- BFLFK.g01 (geometry) ---

Geom Title=Geometry
Program Version=6.10

River Reach=BFLFK           ,Main
Reach XY= 30
2342935.31315118559413.2729799752342784.79990488559262.991115898
2342460.07811342 559392.775961312342242.04016365559363.093934074
2342173.60099608559206.1690510812341847.98091243 559135.33684364
2341577.22357987559393.2401992232341580.75966205559543.332746819
2341069.37092111559725.1886823332341029.84016024 559985.66093041
2338704.39664838560519.2783014922338540.31134668560708.118146911
2338498.58242749560979.0004791622338028.50134666 561295.68882215
2337790.49854182561125.2252523152337252.84016831561424.697094321
2337205.56532848561273.1071743972336885.46787156561361.310081989
2336368.63688423561205.1329008942336059.68310581561464.427985996
2335719.35799906562067.3388536572335636.50022514562024.235265329
2334968.94316135562318.344257161  2334442.435028562838.687376559
2333841.29154523562971.5263497382333800.33427805563213.114121139
  2333635.298847563216.7095864122333557.63496032563527.904173985
2333461.27426066563589.0283955782333568.50928238563808.496788666

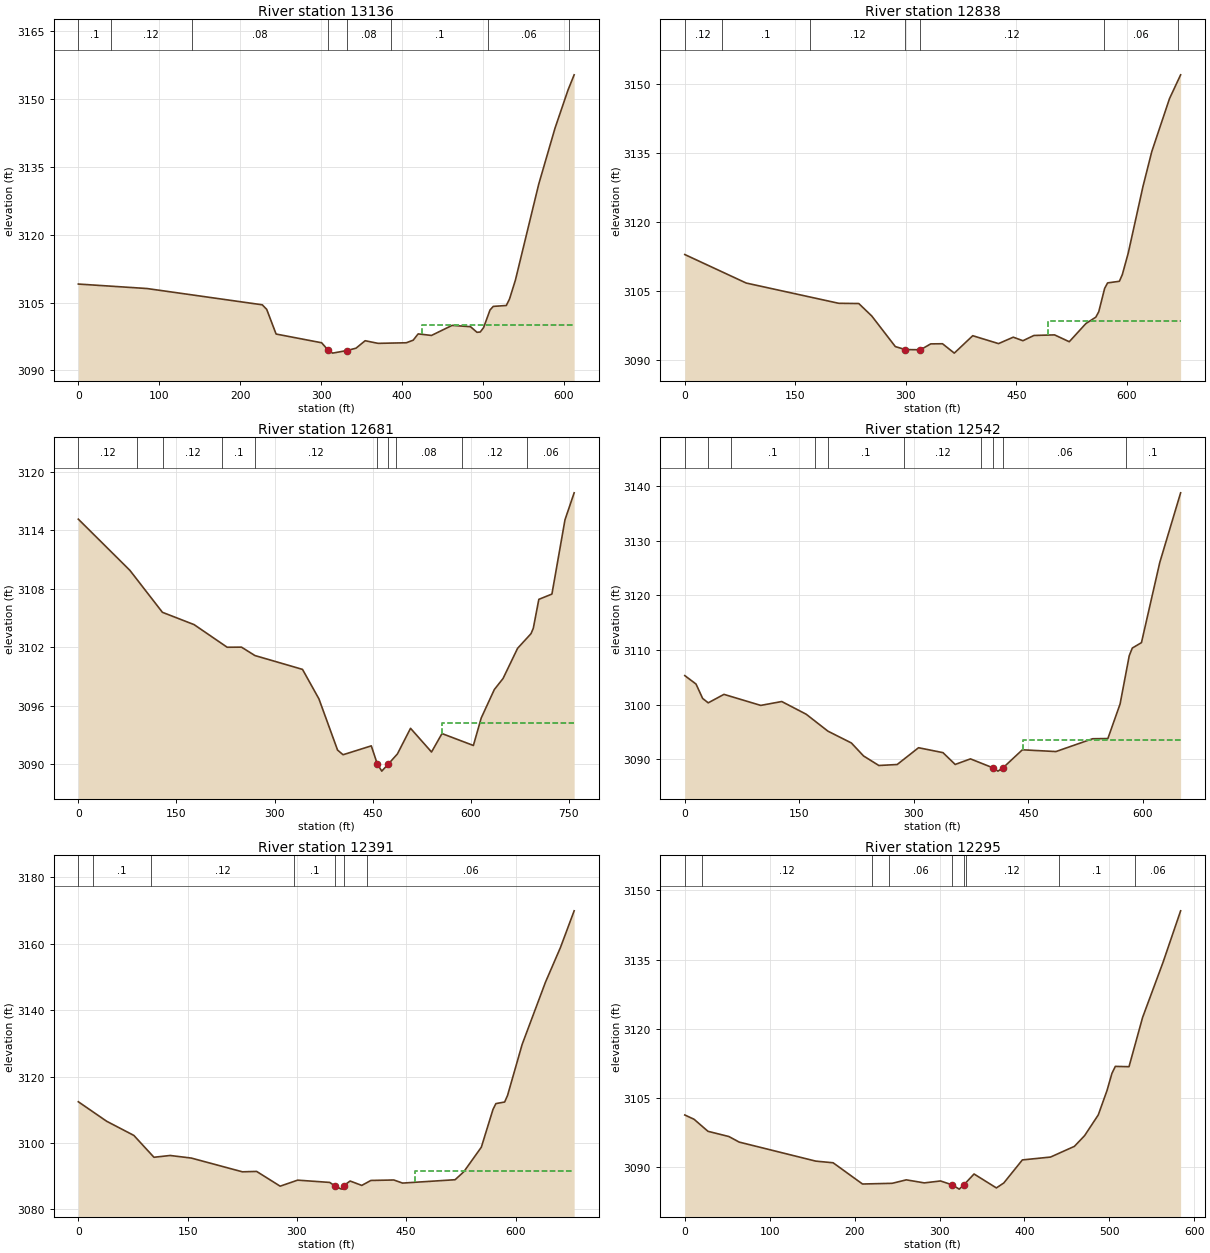
Type RM Length L Ch R = 1 ,13136   ,302.5,297.6,285.5
XS GIS Cut Line= 4
2343081.56004884559138.5378096162342996.34597676559348.732520747
2342831.59877073   559522.9479572342818.34324841559668.758702559
#Sta/Elev= 30
       0 3109.08    84.9 3108.09   227.4 3104.49   232.9 3103.48   244.5 3098.03
   300.8  3096.1   308.6 3094.52   314.4 3093.81     332 3094.38   343.3  3094.9
   354.6 3096.55   370.6 3095.97   405.5  3096.1     414 3096.67   420.1 3098.06
   436.6 3097.72   462.1 3099.94   484.9 3099.65   492.9 3098.41   496.9 3098.48
     501 3099.44     509 3103.35     513 3104.14   529.1 3104.34   533.1 3105.78
   540.4 3109.97   569.2 3131.16   589.3 3143.52   605.4 3151.97     613 3155.33
#Mann= 8 ,-1,0
       0      .1       0      40     .12       0     140     .08       0
   308.6    .045       0     332     .08       0  386.81      .1       0
  506.59     .06       0  606.59      .1       0
#XS Ineff= 2 , 0
                          424.82         3100.09
Permanent Ineff=
       F       F
Bank Sta=308.6,332
XS Rating Curve= 0 ,0
Exp/Cntr=0.3,0.1

Type RM Length L Ch R = 1 ,12838   ,156.9,156.5,153.1
XS GIS Cut Line= 4
 2342858.7911495559032.0027583982342726.23793912559228.461858295
2342725.05299679559400.3241696922342726.02318185559664.214506113
#Sta/Elev= 30
       0 3112.89    83.3 3106.69   208.9 3102.28   236.1 3102.23   253.7 3099.52
   285.7 3092.86   299.3 3092.21   319.83092.175   333.7 3093.45   349.7 3093.48
   365.7 3091.44   390.7 3095.23   425.7 3093.51   445.7 3094.91   458.8 3094.14
   473.7 3095.28   501.7 3095.41   521.7 3093.92   544.3 3097.88   557.7 3099.26
   561.7 3100.44   569.7 3105.52   573.7 3106.72   589.7 3107.07   593.7 3108.53
   601.7  3113.2   621.7 3127.69   633.7 3135.31   657.7 3146.81   672.8 3151.99
#Mann= 7 ,-1,0
       0     .12       0      50      .1       0     170     .12       0
   299.3    .045       0   319.8     .12       0  568.86     .06       0
  668.86      .1       0
#XS Ineff= 2 , 0
                          493.05         3098.53
Permanent Ineff=
       F       F
Bank Sta=299.3,319.8
XS Rating Curve= 0 ,0
Exp/Cntr(USF)=0,0
Exp/Cntr=0.3,0.1

Type RM Length L Ch R = 1 ,12681   ,138,139.1,138.3
XS GIS Cut Line= 3
2342823.04168789558982.1744086722342574.67431244559223.750488705
2342591.16745846559635.108954301
#Sta/Elev= 30
       0 3115.14    78.9 3109.89   128.6 3105.59     177 3104.33   227.6 3102.01
   249.5 3102.02     270 3101.16   342.8 3099.74   367.9 3096.72   396.4 3091.47
   404.8 3090.99     448  3091.9   457.1 3090.06     464 3089.31   474.23090.047
   487.9 3091.07     508  3093.7   540.1 3091.27   556.1 3093.16   604.1 3091.94
   616.1 3094.76   636.1 3097.67   649.5 3098.81   671.7  3101.9   692.2  3103.4
   695.7 3103.95   704.2 3106.92   724.2 3107.46   744.2 3115.08   758.2 3117.84
#Mann= 10 ,-1,0
       0     .12       0      90      .1       0     130     .12       0
     220      .1       0     270     .12       0   457.1    .045       0
   474.2     .12       0  486.48     .08       0  586.48     .12       0
  686.48     .06       0
#XS Ineff= 2 , 0
                          555.96         3094.22
Permanent Ineff=
       F       F
Bank Sta=457.1,474.2
XS Rating Curve= 0 ,0
Exp/Cntr(USF)=0,0
Exp/Cntr=0.3,0.1

Type RM Length L Ch R = 1 ,12542   ,152.7,151.4,152.2
XS GIS Cut Line= 3
2342582.20267919559030.1795524142342457.80859107559170.473636764
2342459.67917886559632.508821222
#Sta/Elev= 30
       0 3105.31    14.7 3103.77    23.4 3101.13    30.7 3100.33    51.3 3101.88
    99.5 3099.86     127 3100.57     159 3098.25   187.5 3095.15   218.2 3092.99
   234.2 3090.61   254.2 3088.87   278.2 3089.05   306.2 3092.12   338.2 3091.22
   354.2 3089.06   374.2 3090.08   403.7 3088.44   410.2 3087.84   416.8 3088.44
   442.2 3091.74   486.2 3091.42   534.2 3093.76   554.2  3093.8   570.2 3100.12
   582.2 3108.95   586.2 3110.35   598.2 3111.34   622.2 3126.01   649.5 3138.74
#Mann= 10 ,-1,0
       0      .1       0      30     .12       0      60      .1       0
     170     .12       0   187.5      .1       0   287.5     .12       0
   387.5     .06       0   403.7    .045       0   416.8     .06       0
   577.5      .1       0
#XS Ineff= 2 , 0
                          443.34          3093.5
Permanent Ineff=
       F       F
Bank Sta=403.7,416.8
XS Rating Curve= 0 ,0
Exp/Cntr(USF)=0,0
Exp/Cntr=0.3,0.1

Type RM Length L Ch R = 1 ,12391   ,88.6,95.7,100.1
XS GIS Cut Line= 3
2342374.45374325 558979.703903532342319.38509451559178.891281825
2342332.12804734559652.572285388
#Sta/Elev= 30
       0  3112.4    38.9 3106.53    76.2 3102.27   103.8 3095.69     126 3096.23
   155.1 3095.45   225.2 3091.31   244.7 3091.43     277 3086.99     301  3088.8
     345 3088.12   352.13087.093     361  3086.1   364.23087.135     373 3088.54
     389 3087.22   401.5 3088.71     433 3088.85     445 3087.92   517.1 3088.93
   529.1 3091.34   553.1 3098.72   569.1 3110.09   573.1 3111.85   585.1 3112.32
   589.1 3114.31   609.1 3129.65   641.1 3148.38   661.7 3158.84   680.5 3169.88
#Mann= 7 ,-1,0
       0     .12       0      20      .1       0     100     .12       0
  296.66      .1       0   352.1    .045       0   364.2      .1       0
  396.66     .06       0
#XS Ineff= 2 , 0
                          462.47         3091.57
Permanent Ineff=
       F       F
Bank Sta=352.1,364.2
XS Rating Curve= 0 ,0
Exp/Cntr(USF)=0,0
Exp/Cntr=0.3,0.1

Type RM Length L Ch R = 1 ,12295   ,265,264.2,258.6
XS GIS Cut Line= 4
2342334.34979684559054.4971937012342296.00274712559231.267739982
2342202.47335755559440.7735726112342217.43805988559613.802943309
#Sta/Elev= 30
       0 3101.34    10.9 3100.41    27.3  3097.8    51.9 3096.67    64.1 3095.46
   154.2 3091.34   174.7 3090.98   209.3 3086.38   244.3 3086.53   260.9 3087.28
   282.1 3086.62   301.2 3087.04   315.13086.181   323.2 3085.27   328.63086.177
   340.7 3088.55     367 3085.53   375.7  3086.6   397.6  3091.6   430.8 3092.22
   458.9 3094.54   470.9 3096.86     487 3101.35   497.3 3106.64   503.1 3110.36
   507.1 3111.87   523.2  3111.8   539.2 3122.47   563.3 3134.43     584 3145.58
#Mann= 9 ,-1,0
       0      .1       0      20     .12       0  220.88      .1       0
  240.88     .06       0   315.1    .045       0   328.6     .06       0
  330.88     .12       0  440.32      .1       0  530.32     .06       0
Bank Sta=315.1,328.6
XS Rating Curve= 0 ,0
Exp/Cntr(USF)=0,0
Exp/Cntr=0.3,0.1

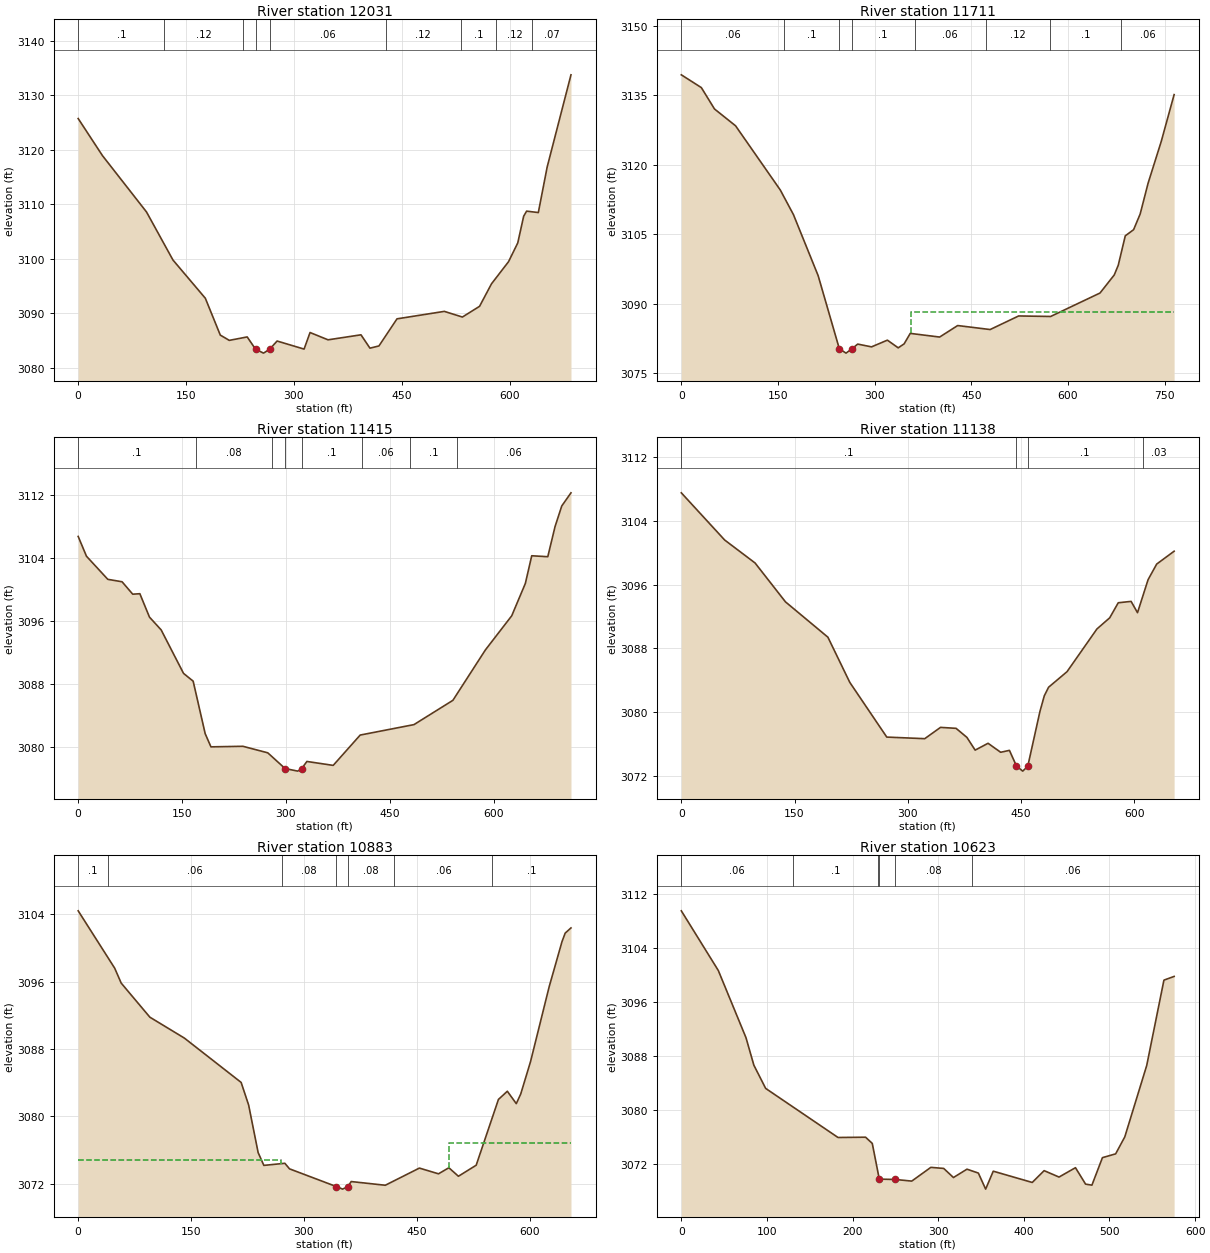
Type RM Length L Ch R = 1 ,12031   ,324.9,320.3,307.6
XS GIS Cut Line= 5
2342100.25381792558952.0986718012342134.21029503559118.000317124
2342074.05882129559328.5304752242342052.82633424559398.685347306
2342098.45978001559617.575840885
#Sta/Elev= 30
       0 3125.73    33.8 3118.92      95 3108.59   131.8 3099.77   176.8 3092.76
   197.6    3086   210.1 3085.03     235 3085.66   246.7  3083.4   257.7 3082.69
   266.23083.404   276.6 3084.91   314.1 3083.43   322.4 3086.47   347.4 3085.13
   393.2 3086.05   405.7  3083.6   418.2 3084.01   443.3 3088.98   509.1 3090.35
   534.2 3089.31   558.1 3091.28   574.7 3095.41   598.4 3099.47   611.2 3102.91
   619.4  3107.8   623.5 3108.74   639.8 3108.48   652.1 3116.84   685.2 3133.75
#Mann= 9 ,-1,0
       0      .1       0     120     .12       0  229.34     .06       0
   246.7    .045       0   266.2     .06       0   428.3     .12       0
  531.59      .1       0  581.59     .12       0  631.59     .07       0
Bank Sta=246.7,266.2
XS Rating Curve= 0 ,0
Exp/Cntr(USF)=0,0
Exp/Cntr=0.3,0.1

Type RM Length L Ch R = 1 ,11711   ,300.7,295.5,283.6
XS GIS Cut Line= 4
2341845.96171201558914.756698304 2341803.1028641559122.773648085
2341891.02049029559399.6206412012341985.77198079559643.840619845
#Sta/Elev= 30
       0 3139.43    31.1 3136.67    51.5 3132.06    84.2 3128.43   153.6 3114.58
     174 3109.27   212.4 3096.08   245.2 3080.33   255.6 3079.38   264.23080.244
   273.7 3081.33   295.2 3080.73   319.8 3082.18   336.6 3080.52   345.8 3081.38
   355.3 3083.64   400.9 3082.85   428.9 3085.33   479.3 3084.47   523.5  3087.4
   573.2 3087.29   649.8 3092.35   671.9 3096.25   678.1 3098.34     689 3104.69
   701.9 3106.01   712.1 3109.39   724.4 3116.04   744.8 3125.05   764.8 3135.16
#Mann= 8 ,-1,0
       0     .06       0     160      .1       0   245.2    .045       0
   264.2      .1       0  362.39     .06       0  472.39     .12       0
  572.86      .1       0  682.86     .06       0
#XS Ineff= 2 , 0
                          356.51          3088.2
Permanent Ineff=
       F       F
Bank Sta=245.2,264.2
XS Rating Curve= 0 ,0
Exp/Cntr(USF)=0,0
Exp/Cntr=0.3,0.1

Type RM Length L Ch R = 1 ,11415   ,277.4,277.7,276.7
XS GIS Cut Line= 3
2341366.79391228559164.5692000222341769.42071233559488.611010186
2341875.17088391559652.572285388
#Sta/Elev= 30
       0 3106.78      12 3104.26    42.8 3101.32    63.4 3101.01    78.8 3099.43
    89.1 3099.49     103 3096.51   119.9 3094.88   152.2 3089.35   166.1 3088.36
   183.5 3081.67   191.8    3080     238 3080.07   273.9 3079.24   298.9 3077.24
   317.2 3076.91   322.9 3077.23   330.4 3078.14   368.4 3077.64   407.4  3081.5
   485.1 3082.83   541.3 3085.92   588.3 3092.34   626.3 3096.68     646  3100.8
   655.2 3104.32   678.4  3104.2   688.9 3108.04   698.6 3110.66   711.9 3112.33
#Mann= 8 ,-1,0
       0      .1       0     170     .08       0     280      .1       0
   298.9    .045       0   322.9      .1       0     410     .06       0
     480      .1       0  546.83     .06       0
Bank Sta=298.9,322.9
XS Rating Curve= 0 ,0
Exp/Cntr(USF)=0,0
Exp/Cntr=0.3,0.1

Type RM Length L Ch R = 1 ,11138   ,252.5,255,250.1
XS GIS Cut Line= 3
2341318.28465926559182.0325311092341431.79631132559406.145280054
2341712.24280855559693.675737122
#Sta/Elev= 30
       0 3107.55    57.4 3101.62    97.7 3098.73     138 3093.84   194.2  3089.4
   223.2 3083.72   272.2 3076.84   322.5 3076.64   343.4 3078.06     364 3077.94
   378.4  3076.8   389.3  3075.2   406.4 3076.06   423.1 3074.93   434.7 3075.17
     4443073.209   452.3 3072.56     4593073.167   475.2 3080.09   480.9 3082.03
   486.6 3083.11     511 3085.06   550.6 3090.43   567.6 3091.84   578.9 3093.73
   595.9  3093.9   604.4 3092.48   618.4 3096.63   629.8 3098.59   652.9 3100.21
#Mann= 4 ,-1,0
       0      .1       0     444    .045       0     459      .1       0
  611.22     .03       0
Bank Sta=444,459
XS Rating Curve= 0 ,0
Exp/Cntr(USF)=0,0
Exp/Cntr=0.3,0.1

Type RM Length L Ch R = 1 ,10883   ,256,259.8,258.4
XS GIS Cut Line= 3
2341133.94949779559337.2621407682341243.58040961559528.388597661
2341563.74147953559822.354670953
#Sta/Elev= 30
       0 3104.41    48.5  3097.6    57.2 3095.82    95.3 3091.77   141.1 3089.29
   216.6 3084.02   226.6 3081.32   239.2 3075.68   246.8 3074.16   274.7 3074.41
   280.9 3073.75     343 3071.65   351.5 3071.34   358.43071.643   362.9 3072.24
   408.2  3071.8   453.5 3073.84   478.9 3073.16   492.7 3073.88   505.4 3072.87
     529 3074.18   558.6    3082   570.4 3082.97   582.3  3081.5   588.2 3082.64
   601.3 3086.51   626.1 3095.42   643.1 3100.76   647.3 3101.76     655 3102.38
#Mann= 7 ,-1,0
       0      .1       0      40     .06       0  270.34     .08       0
     343    .045       0   358.4     .08       0  420.34     .06       0
  550.34      .1       0
#XS Ineff= 2 , 0
          269.95 3074.84  493.02         3076.83
Permanent Ineff=
       F       F
Bank Sta=343,358.4
XS Rating Curve= 0 ,0
Exp/Cntr(USF)=0,0
Exp/Cntr=0.3,0.1

Type RM Length L Ch R = 1 ,10623   ,205.1,211.9,203.9
XS GIS Cut Line= 3
2341028.02927309559463.6423789532341196.35832144559757.864581103
2341344.17668742559942.460722356
#Sta/Elev= 30
       0 3109.52    43.2 3100.67    75.5 3090.71    84.7 3086.63    98.5 3083.18
     183  3075.9   215.2 3075.94     223 3075.02   231.23069.723     250 3069.67
   269.1 3069.43   291.4 3071.47   306.4 3071.31   317.8 3069.96   333.6  3071.2
   346.9 3070.62   355.4 3068.24   364.3  3070.9   409.8 3069.23   423.7 3070.98
   441.1 3070.03   460.3 3071.42   472.1 3068.98   479.5 3068.83   491.8 3072.91
   507.2 3073.47   517.9 3075.99   543.5 3086.58   563.6 3099.24   575.5 3099.79
#Mann= 6 ,-1,0
       0     .06       0     130      .1       0     230     .08       0
   231.2    .045       0     250     .08       0  338.97     .06       0
Bank Sta=231.2,250
XS Rating Curve= 0 ,0
Exp/Cntr(USF)=0,0
Exp/Cntr=0.3,0.1

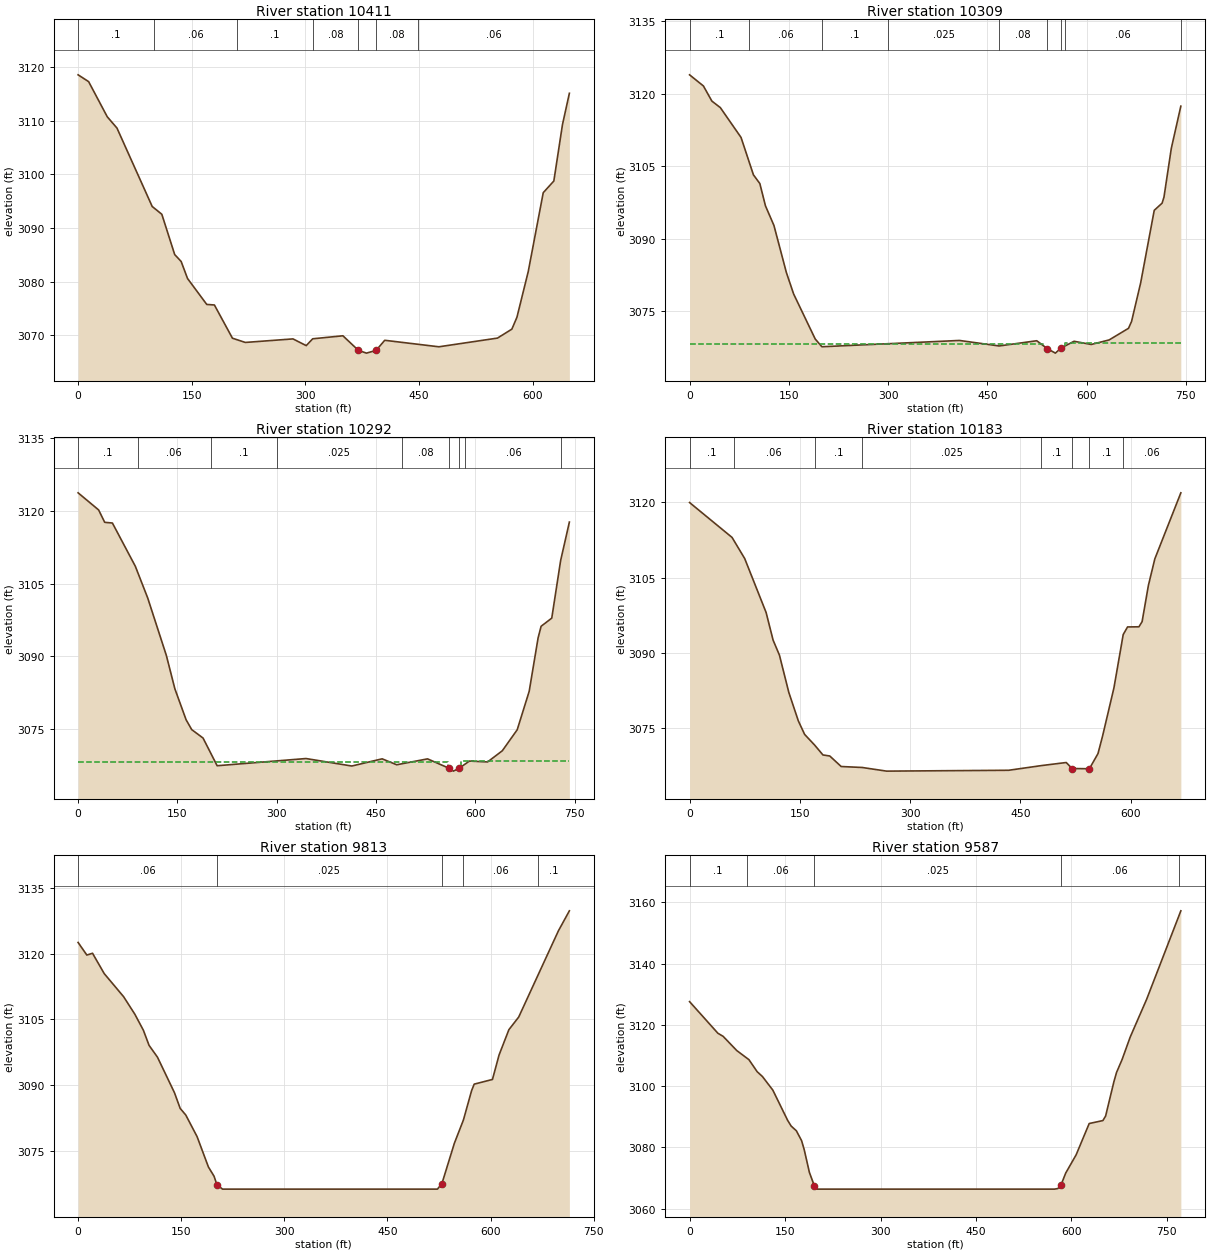
Type RM Length L Ch R = 1 ,10411   ,123.1,101.8,94.1
BEGIN DESCRIPTION:
xs 4
END DESCRIPTION:
XS GIS Cut Line= 3
2340923.61281399559468.7728213012341041.42765398559807.485381873
2341213.12945367560040.951345421
#Sta/Elev= 30
       0 3118.51    13.9 3117.24    38.5 3110.69    51.3 3108.59    97.8 3093.98
   110.5 3092.53   127.5 3085.02     136 3083.74   144.4 3080.57   169.8 3075.73
   179.9 3075.63   203.7 3069.44   220.7 3068.65   283.6 3069.31   301.1 3068.06
   309.6 3069.33   349.5 3069.89     370 3067.17   380.6 3066.66   393.3 3067.17
   404.7 3069.05   476.2 3067.84   553.5 3069.46   572.5 3071.13   579.2 3073.35
   594.1 3081.85   613.9 3096.55   627.9 3098.73   639.3 3109.25   648.4 3115.07
#Mann= 7 ,-1,0
       0      .1       0     100     .06       0     210      .1       0
     310     .08       0     370    .045       0   393.3     .08       0
  448.62     .06       0
Bank Sta=370,393.3
XS Rating Curve= 0 ,0
Exp/Cntr(USF)=0,0
Exp/Cntr=0.5,0.3

Type RM Length L Ch R = 1 ,10309   ,17.4,17.5,16.9
BEGIN DESCRIPTION:
xs 3
END DESCRIPTION:
XS GIS Cut Line= 6
2340839.79710791559477.5887433282340940.37017797559750.027186279
2340963.28556102559864.6041015392340984.29132882559907.252175552
2341116.69131979 559928.257943352341202.62400623560053.656011717
#Sta/Elev= 30
       0 3123.92    20.9 3121.62    33.7 3118.49    46.5 3117.14    77.8 3110.97
    96.5 3103.25   106.2 3101.44   114.7 3096.83   127.5 3092.78   146.3 3083.05
   157.3  3078.6   189.9  3069.3     200  3067.7   407.9    3069   467.9 3067.86
   524.7 3068.94   540.9 3067.29   552.9 3066.38     561 3067.39   581.1 3068.83
   607.2 3068.17   634.2 3069.11   663.4 3071.51     668 3072.91   681.8 3080.91
   702.3  3095.9   714.2 3097.39     717 3098.62   728.1 3108.71   742.5 3117.44
#Mann= 9 ,-1,0
       0      .1       0      90     .06       0     200      .1       0
  300.41    .025       0   467.9     .08       0   540.9    .045       0
     561     .08       0   567.9     .06       0  742.53      .1       0
#XS Ineff= 2 , 0
           534.5 3068.27   567.4         3068.55
Permanent Ineff=
       F       F
Bank Sta=540.9,561
XS Rating Curve= 0 ,0
Exp/Cntr(USF)=0,0
Exp/Cntr=0.5,0.3

Type RM Length L Ch R = 1 ,10292   ,97,108.4,125.5
BEGIN DESCRIPTION:
xs 2
END DESCRIPTION:
XS GIS Cut Line= 6
2340830.24903164559480.1348970012340934.00479379559761.484877805
2340954.37402317559874.7887162282340981.10863673559921.892559169
2341103.32401301559943.5348653842341182.25477685560067.023318497
#Sta/Elev= 30
       0 3123.67      31 3120.15    40.2  3117.6    51.8 3117.46    86.4 3108.57
   105.1 3102.05   133.3 3090.21   146.1 3083.37   163.1 3076.98   171.6 3074.95
   188.7 3073.22     210 3067.52   344.2    3069   413.4 3067.46   459.2 3068.94
   481.2 3067.72   527.8 3068.93   560.3    3067   566.8 3066.41   575.9 3067.03
     591 3068.48   618.5  3068.3   640.7  3070.6   663.2 3074.92   681.3 3082.83
   694.8 3093.84   699.3 3096.21   715.4 3097.89   728.8 3109.74     742 3117.65
#Mann= 9 ,-1,0
       0      .1       0      90     .06       0     200      .1       0
  299.87    .025       0  489.16     .08       0   560.3    .045       0
   575.9     .08       0  584.82     .06       0  730.07      .1       0
#XS Ineff= 2 , 0
           558.1  3068.2   578.1          3068.5
Permanent Ineff=
       F       F
Bank Sta=560.3,575.9
XS Rating Curve= 0 ,0
Exp/Cntr(USF)=0,0
Exp/Cntr=0.5,0.3

Type RM Length L Ch R = 1 ,10183   ,460.2,370.2,373.3
XS GIS Cut Line= 2
2340799.35539826559507.2527240832341040.82367995560130.327129524
#Sta/Elev= 30
       0 3119.97    57.8    3113      75 3108.78   104.1 3098.01   113.6  3092.5
   122.2 3089.51     135 3082.05   147.9 3076.38   156.5 3073.67     170 3071.56
   181.4 3069.57   190.7 3069.36   206.2 3067.26   234.7 3067.07   267.9 3066.34
     434 3066.51   478.3 3067.44   512.3 3068.06   520.3 3066.86   543.83066.814
   555.5 3069.84   561.7 3073.32   577.2 3082.97   589.8 3093.61   595.7 3095.13
   611.2 3095.16   615.5 3096.19   624.1 3103.45   632.8 3108.72   668.2 3121.91
#Mann= 8 ,-1,0
       0      .1       0      60     .06       0     170      .1       0
   234.7    .025       0   478.3      .1       0   520.3    .045       0
   543.8      .1       0     590     .06       0
Bank Sta=520.3,543.8
XS Rating Curve= 0 ,0
Exp/Cntr(USF)=0,0
Exp/Cntr=0.3,0.1

Type RM Length L Ch R = 1 ,9813    ,224.6,225.8,234.1
XS GIS Cut Line= 3
2340522.73290975559612.7946979132340659.52900327560185.203883531
2340728.41214255560290.954055112
#Sta/Elev= 30
       0 3122.54    12.7 3119.67      21 3120.08      38 3115.45    66.2 3110.19
    82.6 3106.19      95 3102.54   103.2 3099.12   115.5 3096.41   140.2 3088.33
   148.5 3084.76   156.7 3083.24   173.1 3078.33   189.6 3071.42   197.8 3069.31
   201.9  3067.4   210.1 3066.38   522.8 3066.38   529.3 3067.65   547.4 3076.83
   560.6 3082.14   572.4 3088.78   576.2 3090.28   602.8 3091.35   612.4 3096.91
   626.7 3102.68     641 3105.56   669.7 3115.32   698.8  3125.2   714.7 3129.74
#Mann= 5 ,-1,0
       0     .06       0   201.9    .025       0   529.3      .1       0
   560.6     .06       0   669.7      .1       0
Bank Sta=201.9,529.3
XS Rating Curve= 0 ,0
Exp/Cntr(USF)=0,0
Exp/Cntr=0.3,0.1

Type RM Length L Ch R = 1 ,9587    ,290.3,267.1,264.5
XS GIS Cut Line= 4
     2340306.347      559669.827     2340410.135      560112.832
2340449.96903023560282.2223895682340502.28177928560415.159166246
#Sta/Elev= 30
       0 3127.62    44.5 3117.29    52.7 3116.29    74.2 3111.63    93.3 3108.66
   106.2 3104.73   114.4 3103.18   130.8 3098.72   154.1 3088.84   159.6 3086.98
   167.8 3085.43     176 3082.21   180.1 3079.29   188.3 3071.81   196.13067.442
   200.6 3066.38   573.4 3066.38   578.6 3066.57   583.4 3067.63     591 3071.63
   607.4 3077.59   627.9 3087.81   649.4 3088.77   653.7 3090.26   666.6 3101.37
   670.9 3104.51   679.5 3108.67   692.4 3116.09   718.2 3128.41   771.9 3157.28
#Mann= 5 ,-1,0
       0      .1       0      90     .06       0   196.1    .025       0
   583.4     .06       0  769.01      .1       0
Bank Sta=196.1,583.4
XS Rating Curve= 0 ,0
Exp/Cntr=0.3,0.1

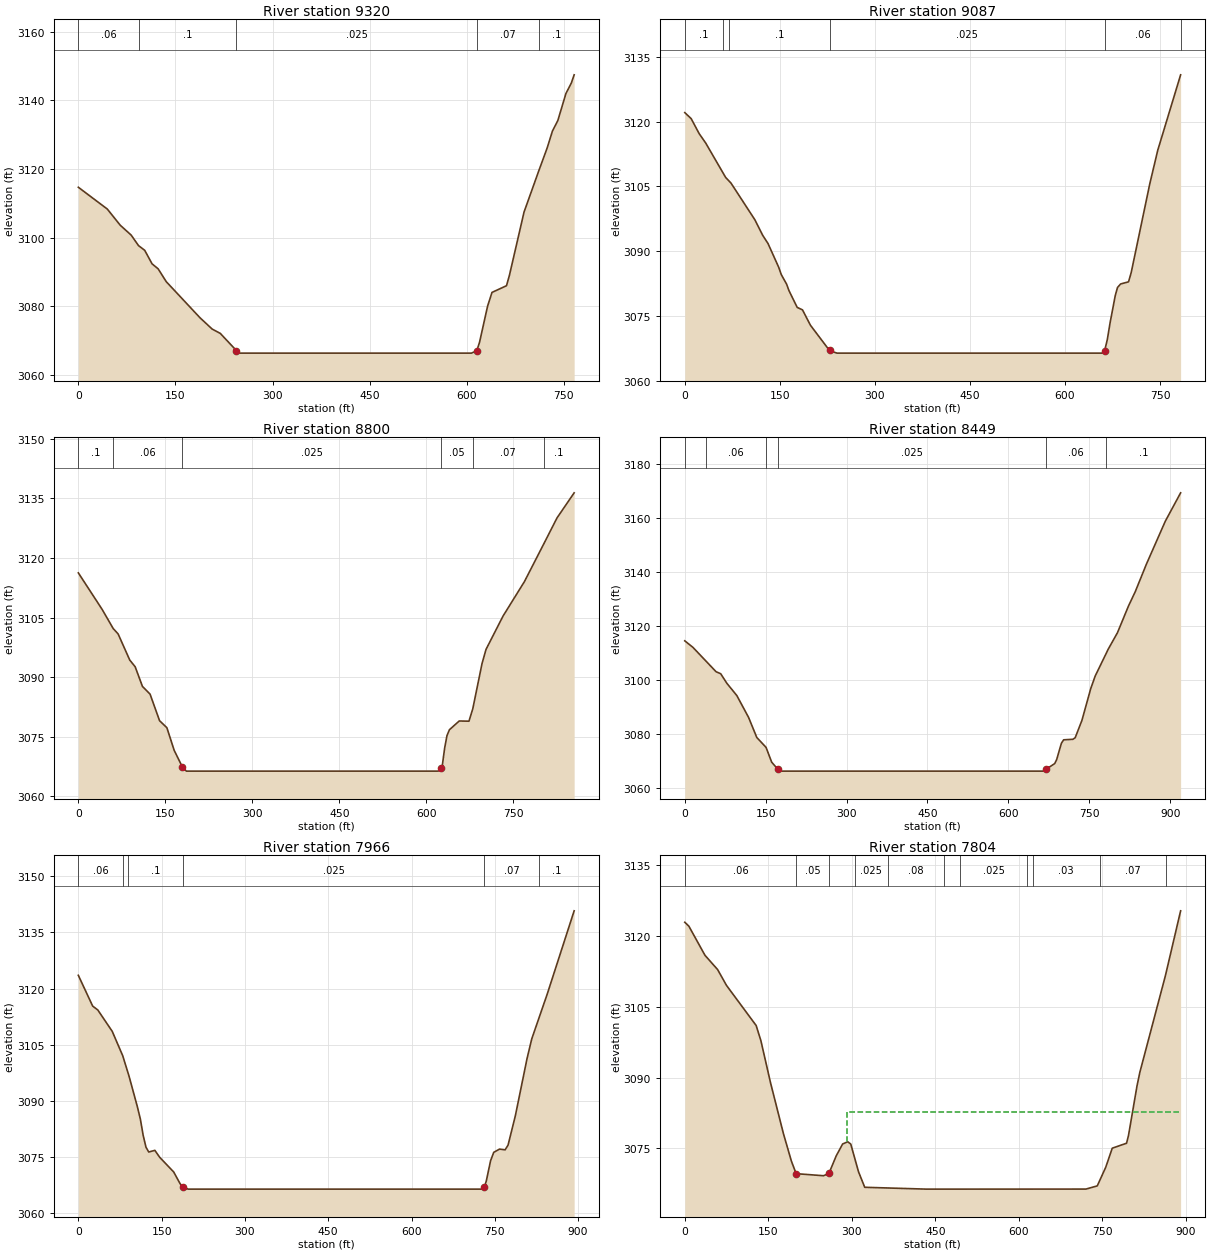
Type RM Length L Ch R = 1 ,9320    ,241.2,232.9,230.2
XS GIS Cut Line= 2
2340030.84908415559770.9348627532340248.17053767560505.364953453
#Sta/Elev= 30
       0  3114.7    44.7 3108.36    64.9 3103.61    81.6 3100.77      93 3097.69
   102.5 3096.34   113.9  3092.4   123.3 3090.93   135.8  3087.2   187.9 3076.69
   206.7 3073.39   219.3 3072.13   244.3  3067.1   244.3 3067.09   248.5 3066.38
   607.2 3066.38   615.5 3067.08   619.7  3069.5   632.2 3080.08     639 3084.07
   661.4 3086.02     666 3089.13   688.5 3107.48     711 3119.35   724.2 3126.14
   732.3 3131.04   740.7 3134.15   753.2 3142.01   761.5 3145.05   765.9 3147.45
#Mann= 5 ,-1,0
       0     .06       0      93      .1       0   244.3    .025       0
   615.5     .07       0     711      .1       0
Bank Sta=244.3,615.5
XS Rating Curve= 0 ,0
Exp/Cntr(USF)=0,0
Exp/Cntr=0.3,0.1

Type RM Length L Ch R = 1 ,9087    ,292.2,286.9,285.3
XS GIS Cut Line= 3
     2339792.751      559799.476     2339925.419      560234.705
2340022.19015277560547.690682393
#Sta/Elev= 30
       0 3122.06    10.1 3120.66    22.7 3117.19      33 3115.02    64.5 3107.05
    72.9 3105.75   110.5 3097.28     123 3093.65   131.4 3091.74   148.1  3086.3
   152.3 3084.56   160.7 3082.35   164.3 3080.89   177.4 3076.97   185.8 3076.39
   198.3 3072.84   228.4 3066.99   240.1 3066.38   658.6 3066.38   662.7 3066.95
   666.9 3069.53   671.1 3073.27   679.5 3079.75     683 3081.58   687.9 3082.39
   700.4 3082.89   704.6 3085.03   733.9 3105.56   746.5 3113.35   782.6 3130.81
#Mann= 6 ,-1,0
       0      .1       0      60     .06       0      70      .1       0
   228.4    .025       0   662.7     .06       0   782.6      .1       0
Bank Sta=228.4,662.7
XS Rating Curve= 0 ,0
Exp/Cntr=0.3,0.1

Type RM Length L Ch R = 1 ,8800    ,368.3,351.4,339
XS GIS Cut Line= 3
2339517.97504376559903.8261129652339735.34618212560581.077686887
2339828.50524141560690.502613677
#Sta/Elev= 30
       0 3116.25      41 3107.07    60.1 3102.25    68.6 3100.89    88.7 3094.31
      98 3092.63   110.6 3087.68   123.7 3085.75   140.1 3079.06   152.7  3077.3
   165.3  3071.6   179.5 3067.41   186.3 3066.38     619 3066.38   623.2 3066.45
   626.2 3067.16   627.4 3067.53   631.6 3072.11   635.7 3075.33     640  3076.8
   656.8 3078.99   673.6 3078.94   680.2 3082.07   696.1 3093.41     703 3096.99
   732.4 3105.39   769.2 3114.04   802.7 3123.56   825.4 3130.06     855 3136.38
#Mann= 6 ,-1,0
       0      .1       0    60.1     .06       0   179.5    .025       0
   626.2     .05       0   680.2     .07       0   802.7      .1       0
Bank Sta=179.5,626.2
XS Rating Curve= 0 ,0
Exp/Cntr(USF)=0,0
Exp/Cntr=0.3,0.1

Type RM Length L Ch R = 1 ,8449    ,502.8,483.2,355.4
XS GIS Cut Line= 3
 2339157.1685284560019.1659006642339420.37983879560690.502613677
2339469.17744128560882.735593175
#Sta/Elev= 30
       0 3114.52    15.1 3112.11      58 3103.11    66.6 3102.37    77.9 3098.86
    96.5  3094.3   118.2 3086.26   133.5 3078.82   150.7 3075.15   161.1 3069.69
   172.6 3067.06   178.3 3066.38   663.8 3066.38   670.5 3067.14     686 3069.18
   689.6 3070.68   698.3 3076.67   702.5 3077.95   719.7 3078.14   723.9 3078.73
   736.3 3085.08   752.7 3096.85     761 3101.52   785.3 3111.49   802.3 3117.53
   822.9 3127.47   835.3 3132.69   855.9 3142.83     891 3158.72   919.4 3169.21
#Mann= 6 ,-1,0
       0      .1       0      40     .06       0     150      .1       0
   172.6    .025       0   670.5     .06       0  781.09      .1       0
Bank Sta=172.6,670.5
XS Rating Curve= 0 ,0
Exp/Cntr(USF)=0,0
Exp/Cntr=0.3,0.1

Type RM Length L Ch R = 1 ,7966    ,143.2,162.1,288.9
XS GIS Cut Line= 2
2338675.27933904560284.7773627432339220.92525778560991.603241211
#Sta/Elev= 30
       0 3123.54    25.8 3115.32    35.1 3114.27    61.1 3108.55      80 3102.02
    91.5 3096.49   106.2 3088.47   111.7 3085.12   116.7 3080.82   121.8  3077.6
   126.8  3076.3   137.8 3076.75   146.4 3074.91   171.7 3070.97   183.4  3067.8
   189.1 3066.88   197.8 3066.38   728.2 3066.38     731 3066.86   734.6 3068.51
   742.4 3073.97   748.1 3076.22   758.5 3077.08   768.6 3076.89   773.9 3078.16
     787 3085.99     808 3101.25   816.5 3106.53   844.4 3118.52   892.9 3140.78
#Mann= 6 ,-1,0
       0     .06       0      80    .025       0      90      .1       0
   189.1    .025       0     731     .07       0     830      .1       0
Bank Sta=189.1,731
XS Rating Curve= 0 ,0
Exp/Cntr(USF)=0,0
Exp/Cntr=0.3,0.1

Type RM Length L Ch R = 1 ,7804    ,132.2,126.8,365.5
XS GIS Cut Line= 3
2338560.14855292560347.243376064 2338726.3585104560591.209345506
2339095.06248887561058.702705176
#Sta/Elev= 30
       0 3122.95     7.2 3122.15    36.2 3115.96      59 3112.92    74.9 3109.57
   128.2 3101.06   136.7 3097.84     154 3088.93     177 3078.22   191.4 3072.34
     200 3069.66   249.2 3069.22   258.9 3069.71     272 3073.43   283.5 3075.95
   292.7 3076.42   298.1 3075.94   312.1 3070.04   323.2 3066.77   433.8 3066.38
   720.5 3066.39   740.9 3067.07   756.2 3071.05   767.8 3075.06   793.5 3076.11
     797 3077.77   812.2 3088.22   817.3 3091.12   863.2  3111.6   890.6 3125.38
#Mann= 11 ,-1,0
       0     .06       0     200     .05       0   258.9     .07       0
   305.2    .025       0   365.2     .08       0   465.2     .03       0
   495.2    .025       0   615.2     .06       0   625.2     .03       0
   745.2     .07       0   865.2     .06       0
#XS Ineff= 2 , 0
                          291.83         3082.78
Permanent Ineff=
       F       F
Bank Sta=200,258.9
XS Rating Curve= 0 ,0
Exp/Cntr(USF)=0,0
Exp/Cntr=0.3,0.1