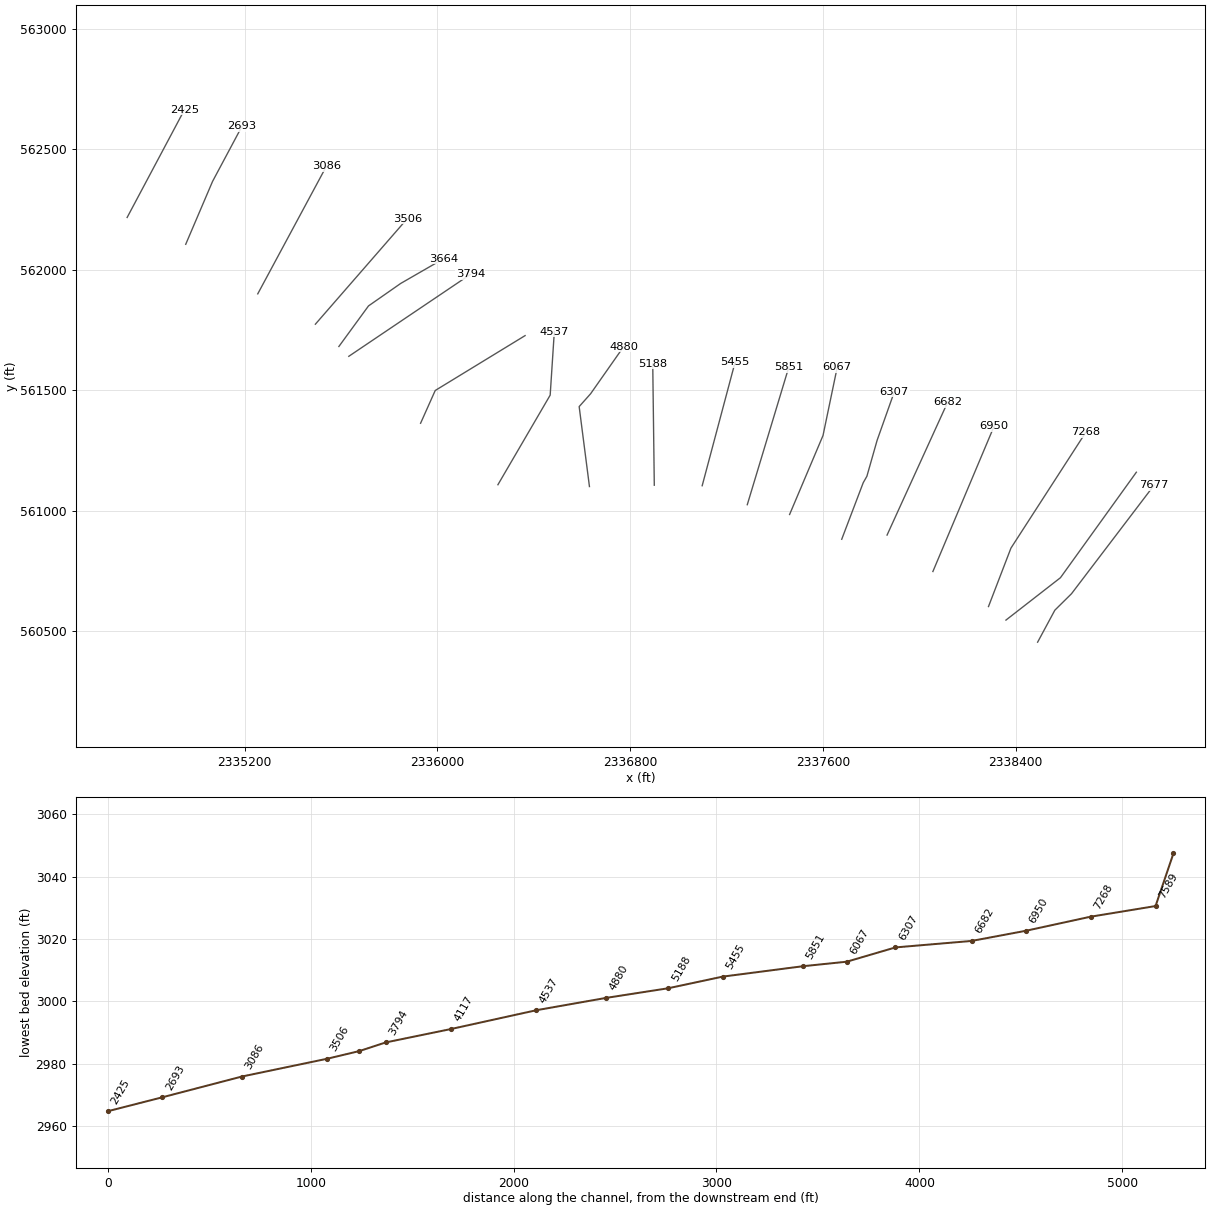
HEC-RAS study BFLFK.prj: BFLFK

--- BFLFK.g01 (geometry) --- (continued)

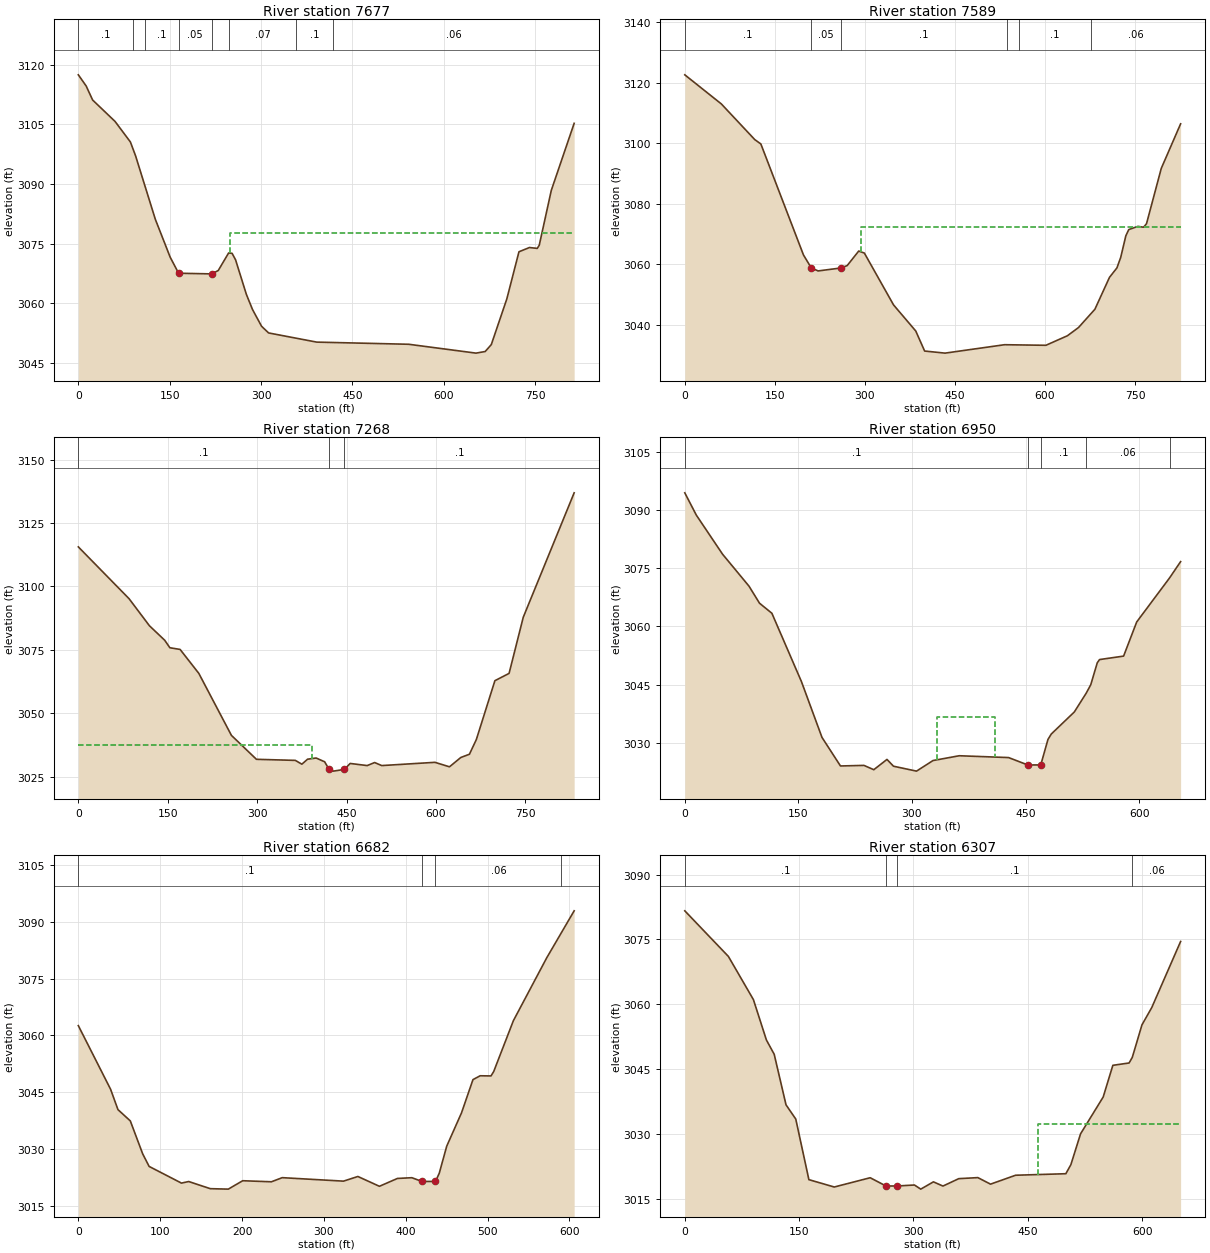
Type RM Length L Ch R = 1 ,7677    ,91.8,88.2,83.7
XS GIS Cut Line= 4
2338491.59297596560453.9121317412338563.10531676560586.720764657
2338632.26010786560655.0897058622338974.89066379561105.381697938
#Sta/Elev= 30
       0 3117.48    12.8 3114.69    23.5 3111.14    60.3 3105.75    85.5 3100.58
      94 3097.09   126.4 3081.13   150.8 3071.59   164.6 3067.56   219.23067.393
   229.7 3068.25   246.7 3072.66   252.4 3072.57   258.1 3070.94   275.8 3062.26
   285.9 3058.44   300.8 3054.22   312.3 3052.54   391.4 3050.23   542.2 3049.69
   652.8 3047.46   667.9 3047.87   677.9 3049.61   703.4 3061.11   723.3 3072.96
   740.5 3074.03   753.3 3073.81   756.6 3074.61   776.4 3088.42   813.9 3105.28
#Mann= 8 ,-1,0
       0      .1       0      90     .06       0     110      .1       0
   164.6     .05       0   219.2      .1       0  248.08     .07       0
  358.08      .1       0  418.08     .06       0
#XS Ineff= 2 , 0
                          249.01         3077.79
Permanent Ineff=
       F       F
Bank Sta=164.6,219.2
XS Rating Curve= 0 ,0
Exp/Cntr(USF)=0,0
Exp/Cntr=0.3,0.1

Type RM Length L Ch R = 1 ,7589    ,317.1,320.4,318.9
XS GIS Cut Line= 3
 2338360.1410211560545.5885214412338586.38445082560721.555633442
2338901.35079415561159.255340605
#Sta/Elev= 30
       0 3122.59    60.9 3112.96   116.6 3101.16   126.7 3099.73   197.7 3063.02
   210.7 3058.74   222.1 3057.75   259.9 3058.72   270.5 3059.52   289.7 3064.32
   299.1 3063.65   347.8 3046.49   384.7 3037.89   399.5 3031.26   433.5 3030.57
   532.6 3033.35   601.5 3033.16   637.3 3036.31   655.8 3039.03   683.1 3045.07
   707.4 3055.62   719.8 3058.75   726.1 3062.21   734.6 3069.33   739.5 3071.42
   754.8 3072.48   764.2  3072.2   769.1 3073.37   793.7 3091.67   825.9 3106.39
#Mann= 6 ,-1,0
       0      .1       0   210.7     .05       0   259.9      .1       0
  536.62     .06       0  556.62      .1       0  676.62     .06       0
#XS Ineff= 2 , 0
                          292.96         3072.31
Permanent Ineff=
       F       F
Bank Sta=210.7,259.9
XS Rating Curve= 0 ,0
Exp/Cntr(USF)=0,0
Exp/Cntr=0.3,0.1

Type RM Length L Ch R = 1 ,7268    ,313.6,317.8,318.6
XS GIS Cut Line= 3
2338287.68397498560601.7797000632338380.84303428560844.288997275
2338691.37323193561324.871446018
#Sta/Elev= 30
       0 3115.62    85.1 3095.19   119.3 3084.51     145 3078.77   153.6 3075.83
   170.8 3075.16   202.2 3065.71   256.9 3041.25   298.9 3031.81   364.1 3031.39
   375.1 3029.89   384.7 3031.86     399 3032.32   413.3 3030.84   420.7 3027.85
   428.1 3027.15   446.6 3027.84   456.1 3030.18   484.7 3029.34   497.2 3030.54
   509.1 3029.34   598.4 3030.62   622.8 3028.85   641.8 3032.53   656.3 3033.82
   667.9 3039.63     699 3062.83   722.8 3065.71   746.6 3087.86     832 3136.95
#Mann= 3 ,-1,0
       0      .1       0   420.7    .045       0   446.6      .1       0
#XS Ineff= 2 , 0
          392.68 3037.49
Permanent Ineff=
       F       F
Bank Sta=420.7,446.6
XS Rating Curve= 0 ,0
Exp/Cntr(USF)=0,0
Exp/Cntr=0.3,0.1

Type RM Length L Ch R = 1 ,6950    ,265.2,268.3,264.8
XS GIS Cut Line= 2
2338056.87796943560747.1539684782338311.06645525561350.609076029
#Sta/Elev= 30
       0  3094.5    15.2 3088.75    49.9 3078.65    84.7 3070.43    98.7    3066
     115 3063.41   154.1 3045.74   181.2 3031.35   205.6 3023.98   236.6 3024.13
   249.6 3023.02     267 3025.67   275.6 3023.92     306 3022.65   327.8 3025.38
   362.4 3026.62   427.6 3026.15     453 3024.24   470.1 3024.25   479.6 3030.83
     484 3032.23   514.4 3037.92   530.1 3042.77   536.1 3044.94   544.7 3050.61
   547.7 3051.45   579.5 3052.35   596.8 3061.16   640.2 3072.53   654.8 3076.74
#Mann= 5 ,-1,0
       0      .1       0     453    .045       0   470.1      .1       0
   530.1     .06       0   640.2      .1       0
#XS Ineff= 1 ,-1
  332.56   409.3 3036.66
Permanent Ineff=
       F
Bank Sta=453,470.1
XS Rating Curve= 0 ,0
Exp/Cntr(USF)=0,0
Exp/Cntr=0.3,0.1

Type RM Length L Ch R = 1 ,6682    ,367.6,375.5,368.3
XS GIS Cut Line= 2
 2337866.7216976560898.5028378962338117.99962824561449.567952186
#Sta/Elev= 30
       0 3062.59    39.4 3045.78    48.4  3040.4    63.5 3037.41    78.6 3028.71
    86.5 3025.38     126 3020.97   134.8 3021.39   161.2  3019.5   183.2 3019.38
   200.8  3021.6   235.9 3021.32   249.1 3022.41   323.9 3021.49   341.5 3022.72
   367.8 3020.13   389.8  3022.2   407.4  3022.4   419.8 3021.41   436.3 3021.41
   440.9 3023.57     450 3030.72   468.1 3039.54   482.1 3048.33   490.9 3049.34
   504.1  3049.3   507.4 3050.45   531.5 3063.92   572.3 3080.56   605.7 3092.94
#Mann= 4 ,-1,0
       0      .1       0   419.8    .045       0   436.3     .06       0
     590      .1       0
Bank Sta=419.8,436.3
XS Rating Curve= 0 ,0
Exp/Cntr(USF)=0,0
Exp/Cntr=0.3,0.1

Type RM Length L Ch R = 1 ,6307    ,237.4,239.7,240.2
XS GIS Cut Line= 5
2337678.50579589 560881.039506812337767.76282144561115.824291419
2337782.94203202561142.4812585172337825.37105799561291.710308459
2337896.74006071561492.882077124
#Sta/Elev= 30
       0 3081.61    57.2 3071.07      90  3061.1   107.1 3051.75   117.3 3048.46
   132.8 3036.78   145.6 3033.49   162.8 3019.49   196.1 3017.79   243.2 3019.93
     264 3018.02   278.9 3018.03   301.3 3018.25   309.6  3017.3   326.2 3018.98
   338.7 3018.01   359.5 3019.72   384.5 3019.96   401.1 3018.45     434 3020.51
   499.9 3020.86   506.5 3022.94   519.2 3030.07   548.9 3038.58   561.6 3045.91
   582.9 3046.45   587.1 3047.75   599.8 3055.27   612.6 3059.24   650.5 3074.53
#Mann= 4 ,-1,0
       0      .1       0     264    .045       0   278.9      .1       0
     587     .06       0
#XS Ineff= 2 , 0
                          463.95         3032.24
Permanent Ineff=
       F       F
Bank Sta=264,278.9
XS Rating Curve= 0 ,0
Exp/Cntr(USF)=0,0
Exp/Cntr=0.3,0.1

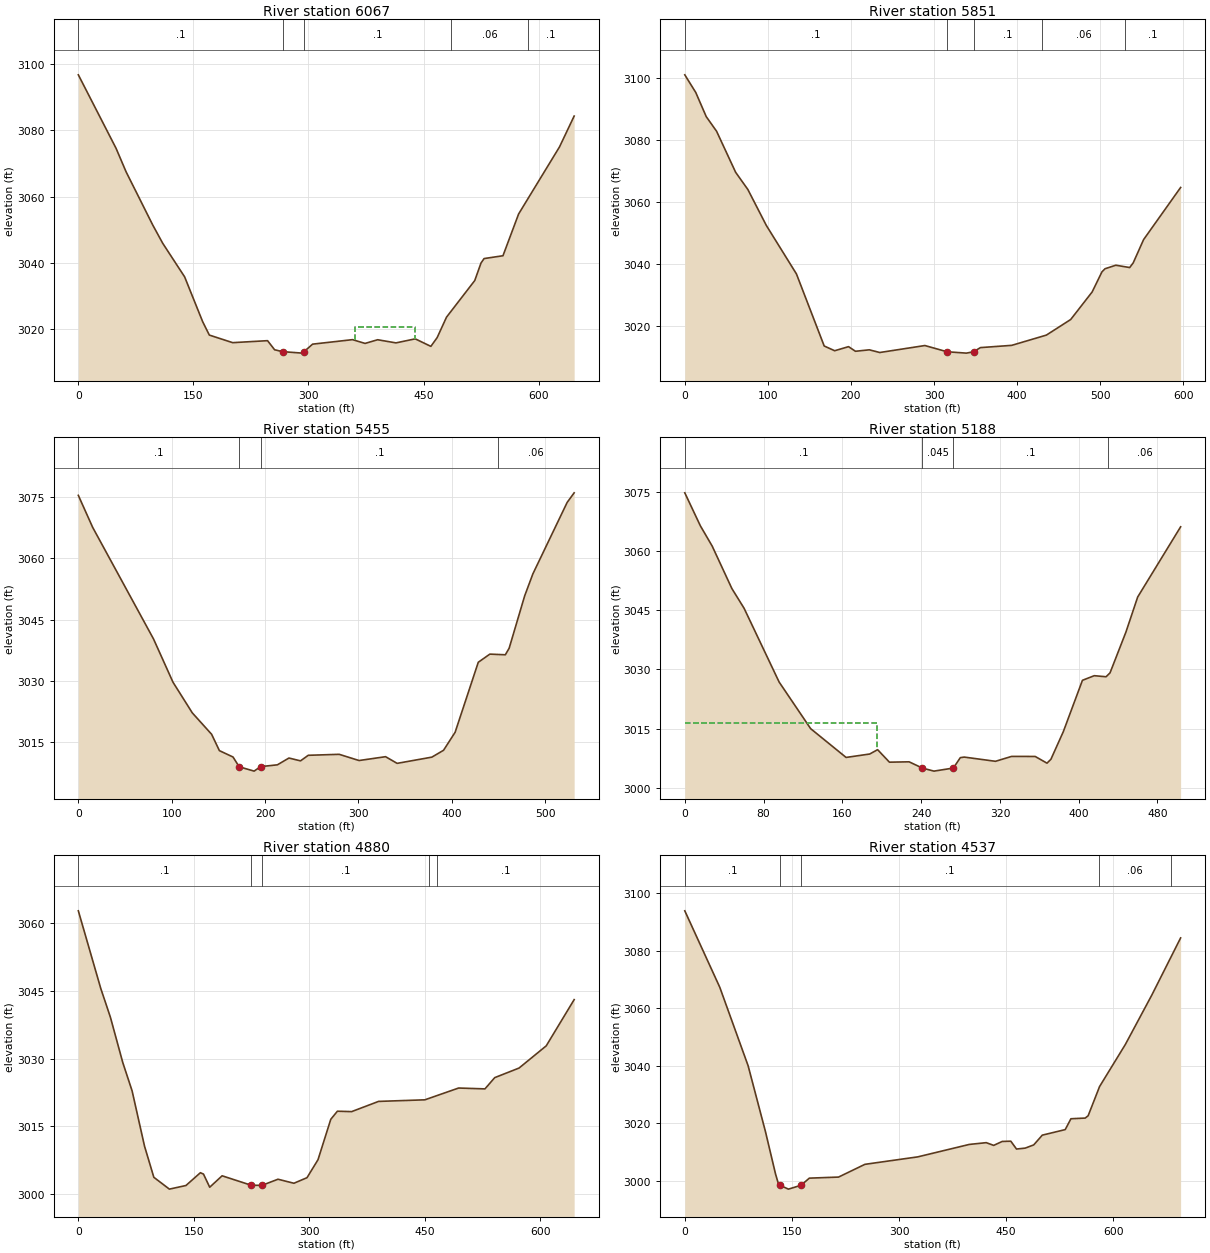
Type RM Length L Ch R = 1 ,6067    ,213.2,216.1,218
XS GIS Cut Line= 3
2337462.15452743560983.8791232092337600.89099106561311.801673614
2337660.07227974561596.065896303
#Sta/Elev= 30
       0 3096.74    49.2 3074.55    62.2 3067.49    97.1 3051.36     110 3045.89
   138.6 3035.74   162.1 3022.21   170.8 3018.17   201.2 3015.88   246.7 3016.48
   255.9 3013.73   266.4 3013.16   292.2 3012.72   294.43013.198   305.4 3015.43
   357.5 3016.79   373.8 3015.65   390.2 3016.76   414.1 3015.81   439.2 3017.03
   459.6 3014.76   467.8 3017.41     480 3023.58   516.8 3034.63     525 3039.94
     529 3041.27   553.6 3042.12     574 3054.73   627.3 3074.98   646.4 3084.29
#Mann= 5 ,-1,0
       0      .1       0   266.4    .045       0   294.4      .1       0
  486.06     .06       0  586.06      .1       0
#XS Ineff= 1 ,-1
  360.47  439.533020.729
Permanent Ineff=
       F
Bank Sta=266.4,294.4
XS Rating Curve= 0 ,0
Exp/Cntr(USF)=0,0
Exp/Cntr=0.3,0.1

Type RM Length L Ch R = 1 ,5851    ,383.5,395.7,395.5
XS GIS Cut Line= 2
2337286.48789036561024.5165835882337458.96523443561595.847785807
#Sta/Elev= 30
       0 3101.15    13.2 3095.45    25.8 3087.65    38.3 3082.91    61.2 3069.67
    75.9 3064.12    98.2 3052.48   134.4 3036.84   167.8 3013.57   180.4 3012.04
   197.1 3013.36   205.4 3011.87   222.1 3012.34   234.7 3011.47     289 3013.72
   315.7 3011.71   338.9 3011.27   347.5  3011.7   355.8 3013.05   393.5 3013.78
   435.2 3017.09   464.5 3022.13   490.3 3031.02   502.1 3037.51   505.8 3038.52
   518.8 3039.66   535.5 3038.91   539.7  3040.4   552.2 3047.92   596.8 3064.77
#Mann= 5 ,-1,0
       0      .1       0   315.7    .045       0   347.5      .1       0
     430     .06       0     530      .1       0
Bank Sta=315.7,347.5
XS Rating Curve= 0 ,0
Exp/Cntr(USF)=0,0
Exp/Cntr=0.3,0.1

Type RM Length L Ch R = 1 ,5455    ,259.2,267.4,271.8
XS GIS Cut Line= 2
2337099.30531485561103.2118856342337236.10140836 561616.43978257
#Sta/Elev= 30
       0 3075.36    15.4 3067.52    80.6 3040.22   101.4 3029.67   122.1 3022.17
   142.8 3016.93   151.1 3012.94   165.7 3011.38   172.3 3008.99   188.3 3007.93
   195.2 3009.03   213.2 3009.47   225.6 3011.13     238 3010.44   246.3  3011.8
   279.4 3012.04   300.7 3010.52   329.1 3011.46   341.5 3009.83   378.7 3011.35
   391.2 3013.03   403.6 3017.43   428.4 3034.55   440.8 3036.54   457.4 3036.38
   461.5    3038   478.1 3050.79   486.9 3056.17   523.6 3073.63   531.1 3075.98
#Mann= 4 ,-1,0
       0      .1       0   172.3    .045       0   195.2      .1       0
     450     .06       0
Bank Sta=172.3,195.2
XS Rating Curve= 0 ,0
Exp/Cntr(USF)=0,0
Exp/Cntr=0.3,0.1

Type RM Length L Ch R = 1 ,5188    ,304.3,307.6,309.4
XS GIS Cut Line= 2
2336900.56983301561105.3653386192336894.10193261561608.783586611
#Sta/Elev= 30
       0 3074.78    15.8 3066.42    27.8 3061.28    47.8 3050.51    60.2 3045.51
    95.8  3026.8   127.8 3014.98   163.8 3007.68   187.8 3008.55   195.8 3009.65
   207.8 3006.48   227.8 3006.57   241.1    3005     253 3004.21   272.7 3004.99
   279.8 3007.63   283.8 3007.77   315.5  3006.7   331.8 3007.94   355.8 3007.93
   367.8 3006.23   371.8 3007.22   384.4 3014.23   403.8 3027.24   415.8 3028.41
   427.8 3028.14   431.8 3029.12   447.9 3039.43   459.9 3048.36   503.5 3066.16
#Mann= 4 ,-1,0
       0      .1       0   241.1    .045       0   272.7      .1       0
     430     .06       0
#XS Ineff= 2 , 0
          195.35 3016.39
Permanent Ineff=
       F       F
Bank Sta=241.1,272.7
XS Rating Curve= 0 ,0
Exp/Cntr(USF)=0,0
Exp/Cntr=0.3,0.1

Type RM Length L Ch R = 1 ,4880    ,354.9,343.3,324.7
XS GIS Cut Line= 4
 2336631.4051886561099.8595079732336588.71704594561431.662798622
 2336636.2561139561485.0229769422336773.05220741561680.030174078
#Sta/Elev= 30
       0 3062.68    29.1 3045.53    41.7 3039.12    57.8 3029.08    69.9 3022.82
      86 3010.61    98.1 3003.72   118.3  3001.1   139.8  3001.9   158.6 3004.73
   162.6 3004.43   170.7 3001.52   186.8 3004.05   224.6 3001.96   238.5 3001.93
   259.4 3003.29   280.1  3002.4   297.1 3003.63   311.4 3007.61     328 3016.55
   336.6 3018.34   355.1 3018.25   390.1 3020.51   450.2 3020.86   494.1 3023.47
   528.3 3023.28     541 3025.77   572.6 3027.89   607.9  3032.8   644.2 3043.03
#Mann= 5 ,-1,0
       0      .1       0   224.6    .045       0   238.5      .1       0
     456     .06       0     466      .1       0
Bank Sta=224.6,238.5
XS Rating Curve= 0 ,0
Exp/Cntr(USF)=0,0
Exp/Cntr=0.3,0.1

Type RM Length L Ch R = 1 ,4537    ,427.1,419.2,411
XS GIS Cut Line= 3
2336251.48936232561107.3584215742336468.41409845 561479.20186658
2336485.61090481561742.469366324
#Sta/Elev= 30
       0 3093.93      49 3067.34    88.7 3040.03     113  3017.1   127.1 3002.38
   130.5  2999.5   133.4 2998.47   145.1 2997.15   162.7 2998.48   174.4 3000.97
   215.3 3001.34   252.2 3005.77   326.3 3008.37   398.3 3012.69   422.1 3013.31
   432.5 3012.36   444.5 3013.73   456.5 3013.82   464.5 3011.09   476.6 3011.41
   488.6 3012.53   500.6 3015.92   532.7 3017.85   540.7 3021.62   560.7 3021.86
   564.8 3022.66   580.8 3032.82   616.9 3047.45   654.1  3064.7   694.3 3084.51
#Mann= 5 ,-1,0
       0      .1       0   133.4    .045       0   162.7      .1       0
  580.49     .06       0  680.49      .1       0
Bank Sta=133.4,162.7
XS Rating Curve= 0 ,0
Exp/Cntr(USF)=0,0
Exp/Cntr=0.3,0.1

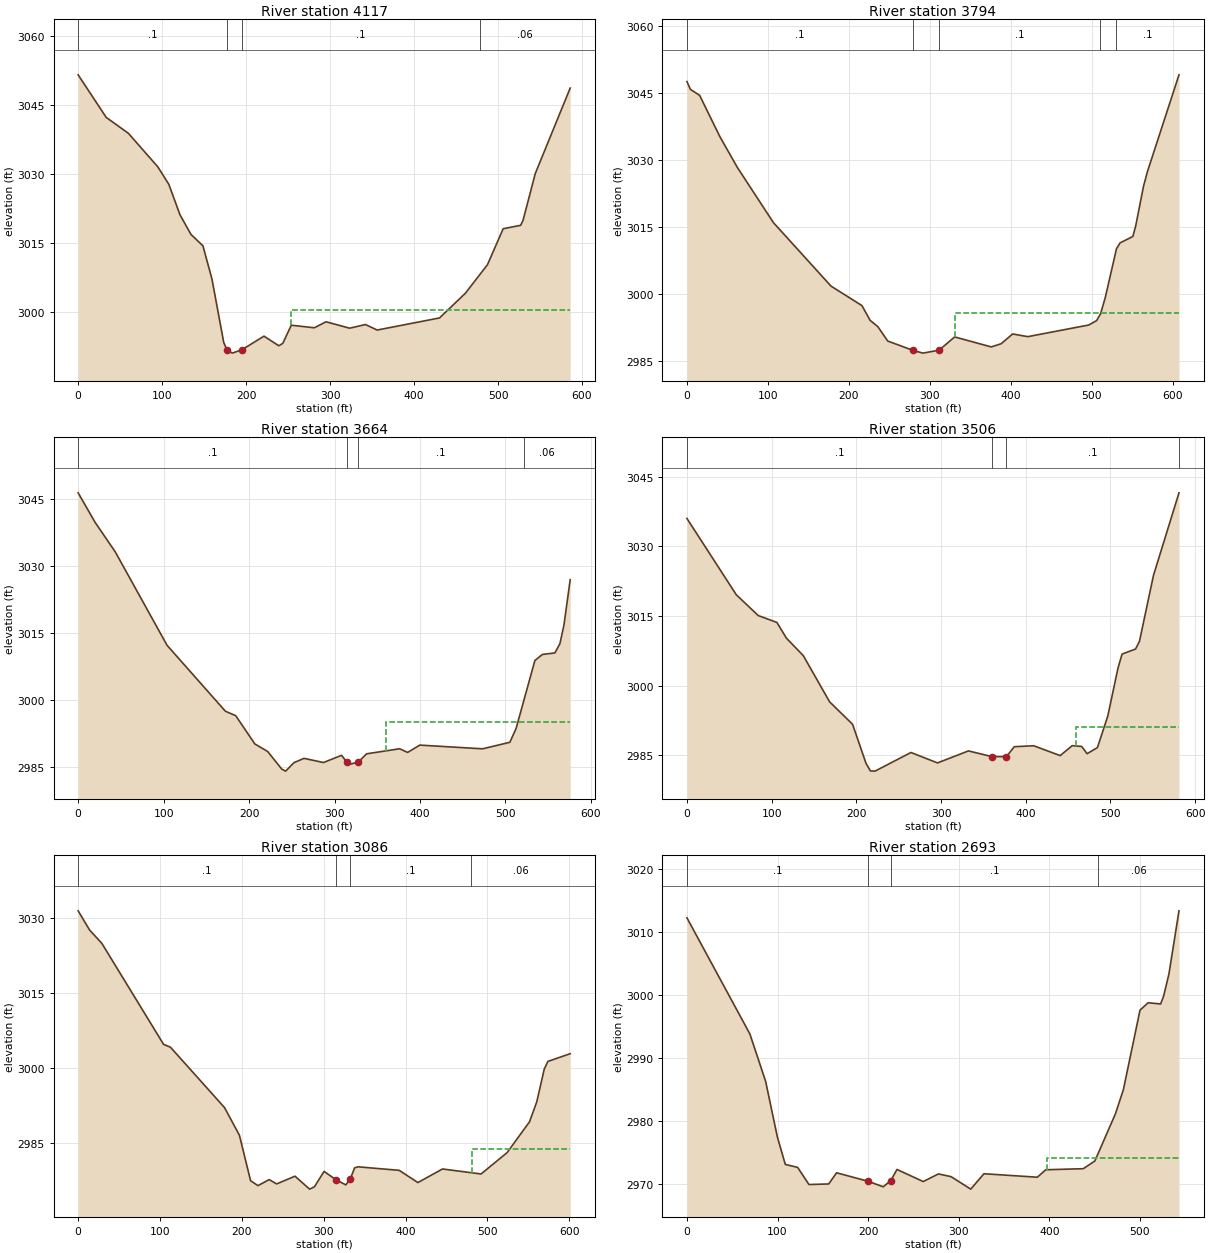
Type RM Length L Ch R = 1 ,4117    ,321.7,323,324.7
XS GIS Cut Line= 3
2335930.56187427561362.5547253212335991.28227059 561498.48636447
2336364.23832871 561726.25965029
#Sta/Elev= 30
       0 3051.65    33.4  3042.4    59.8 3038.94    94.9 3031.64     108 3027.84
   121.2 3021.25   134.3 3016.96   148.6 3014.47   159.3 3007.29   173.4 2993.43
   177.1 2991.88   183.5 2991.14   195.1 2991.88   221.3 2994.83     239 2992.74
   243.7 2993.27   253.8 2997.21   281.2 2996.65   295.2 2997.95   323.3 2996.56
   342.1 2997.36   356.1 2996.16   430.3 2998.79     461 3004.14   487.4 3010.36
   506.1 3018.19   526.9 3018.93   529.8 3020.03   544.3 3030.17   585.9 3048.77
#Mann= 4 ,-1,0
       0      .1       0   177.1    .045       0   195.1      .1       0
  478.88     .06       0
#XS Ineff= 2 , 0
                          253.86         3000.46
Permanent Ineff=
       F       F
Bank Sta=177.1,195.1
XS Rating Curve= 0 ,0
Exp/Cntr(USF)=0,0
Exp/Cntr=0.3,0.1

Type RM Length L Ch R = 1 ,3794    ,130.3,130,130.2
XS GIS Cut Line= 2
2335632.61965624561640.426133004  2336136.478178561979.982962887
#Sta/Elev= 30
       0 3047.62     4.3 3045.89    15.7 3044.54    40.6 3035.32    62.2 3028.42
   106.8 3016.04   177.9 3001.83   216.1 2997.46   226.2 2994.16   235.8 2992.74
     248 2989.52   279.2 2987.44   291.3 2986.82   311.4 2987.48   330.6 2990.45
   375.7 2988.21   387.9 2988.91   402.2 2991.11   420.9 2990.51   496.3 2993.12
   505.9 2994.11   510.8 2995.64   516.7 2999.36   530.4 3010.18   534.9 3011.51
   550.6 3012.94   554.2 3015.34   563.8  3024.2   568.6 3027.44   607.6 3049.14
#Mann= 5 ,-1,0
       0      .1       0   279.2    .045       0   311.4      .1       0
     510     .06       0     530      .1       0
#XS Ineff= 2 , 0
                           331.4         2995.71
Permanent Ineff=
       F       F
Bank Sta=279.2,311.4
XS Rating Curve= 0 ,0
Exp/Cntr(USF)=0,0
Exp/Cntr=0.3,0.1

Type RM Length L Ch R = 1 ,3664    ,154.6,158.4,162
XS GIS Cut Line= 4
2335591.44413019561681.1492622932335714.34174808561849.502163513
2335848.18230455 561942.938023692336024.95285083562044.791528928
#Sta/Elev= 30
       0  3046.4    19.8  3039.8    43.5 3033.15     104 3012.25   172.3 2997.47
   184.4 2996.47   206.7 2990.15   221.8 2988.44   238.3 2984.49   242.8 2984.05
   252.6 2985.96   264.3 2986.91   287.1 2985.98   308.2 2987.59   314.1 2986.14
   318.7 2985.61   327.8 2986.09   337.5 2987.93   376.2 2989.06   385.5 2988.24
   399.7 2989.88   473.2 2989.05   505.1 2990.51   512.4  2993.6   534.4 3008.83
   543.2 3010.19   557.8 3010.53   563.7 3012.62   568.4 3016.77   575.7 3026.93
#Mann= 4 ,-1,0
       0      .1       0   314.1    .045       0   327.8      .1       0
  521.67     .06       0
#XS Ineff= 2 , 0
                          360.34         2994.95
Permanent Ineff=
       F       F
Bank Sta=314.1,327.8
XS Rating Curve= 0 ,0
Exp/Cntr(USF)=0,0
Exp/Cntr=0.3,0.1

Type RM Length L Ch R = 1 ,3506    ,415.1,420.5,420.1
XS GIS Cut Line= 2
2335493.87600532561773.6930608612335875.42104535562211.830905872
#Sta/Elev= 30
       0 3035.98    58.3 3019.55    84.2 3015.08   106.2  3013.6   117.5 3010.21
   137.4 3006.45   168.5  2996.5   195.6 2991.67   211.5 2983.23   216.7 2981.63
   222.1 2981.59   264.5  2985.6   295.9 2983.36   332.4 2985.94     360 2984.72
   377.32984.714   386.5 2986.85   409.5 2987.05   440.7 2984.93   454.9 2987.07
   466.1 2986.91   472.5 2985.34   484.7 2986.66   496.9 2993.43     509 3003.78
   513.8 3006.79   529.7 3007.87   534.3 3009.51   550.9 3023.74     581  3041.5
#Mann= 4 ,-1,0
       0      .1       0     360    .045       0   377.3      .1       0
  580.98     .06       0
#XS Ineff= 2 , 0
                          459.38         2991.17
Permanent Ineff=
       F       F
Bank Sta=360,377.3
XS Rating Curve= 0 ,0
Exp/Cntr(USF)=0,0
Exp/Cntr=0.3,0.1

Type RM Length L Ch R = 1 ,3086    ,390.8,392.1,392.9
XS GIS Cut Line= 2
2335254.72576492561899.6576913022335539.51536418562429.074254023
#Sta/Elev= 30
       0  3031.4      14 3027.57      29  3024.9   104.4 3004.76   112.8 3004.19
   178.9 2992.14   197.1 2986.61   210.7 2977.56   219.7 2976.58   233.4 2977.78
   242.5 2976.92     265 2978.46   282.8 2975.88   288.7 2976.34   300.5 2979.42
   314.7 2977.78   327.1 2976.72   332.4 2977.87   337.8 2980.12   341.8 2980.33
   392.3 2979.63   415.1 2977.19   445.2  2979.9   492.3  2978.9   524.1 2983.16
   551.5 2989.31   560.4 2993.31   569.5 2999.82     574 3001.36   601.2  3002.9
#Mann= 4 ,-1,0
       0      .1       0   314.7    .045       0   332.4      .1       0
     480     .06       0
#XS Ineff= 2 , 0
                          480.73         2983.89
Permanent Ineff=
       F       F
Bank Sta=314.7,332.4
XS Rating Curve= 0 ,0
Exp/Cntr(USF)=0,0
Exp/Cntr=0.3,0.1

Type RM Length L Ch R = 1 ,2693    ,270.3,268.8,267
XS GIS Cut Line= 3
2334955.72790302562105.2706703572335067.11952106562366.382205125
2335189.29097311562595.154237881
#Sta/Elev= 30
       0 3012.25    69.5 2993.83    86.9  2986.3    99.9 2977.45   108.6 2973.14
   122.2 2972.67   134.7 2969.95   156.5 2970.04   165.2 2971.81   199.9 2970.47
   216.7 2969.59     2252970.571   231.9 2972.34   260.8 2970.42   277.7 2971.63
   291.6  2971.2   313.3 2969.22   327.9 2971.66   386.8 2971.11   396.1 2972.29
   437.5 2972.46   450.3 2973.68     473 2981.15   481.8 2984.99   500.2 2997.62
   509.2 2998.78   522.9 2998.59   526.2 2999.81   532.1 3003.34   543.2 3013.36
#Mann= 4 ,-1,0
       0      .1       0   199.9    .045       0     225      .1       0
  453.88     .06       0
#XS Ineff= 2 , 0
                          397.52         2974.11
Permanent Ineff=
       F       F
Bank Sta=199.9,225
XS Rating Curve= 0 ,0
Exp/Cntr(USF)=0,0
Exp/Cntr=0.3,0.1

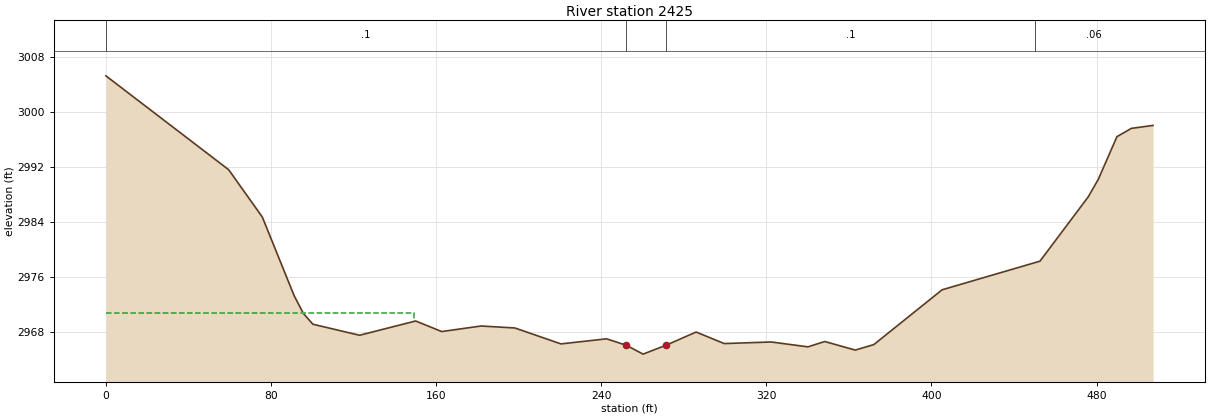
Type RM Length L Ch R = 1 ,2425    ,251.3,253.8,253.3
XS GIS Cut Line= 2
2334712.58275826562216.6622884012334950.93686568562664.624279241
#Sta/Elev= 30
       0 3005.32    59.5 2991.63    75.8 2984.73    91.2 2973.28    95.7 2970.67
   100.3 2969.11   122.9  2967.5   150.1 2969.58   162.7 2968.04   181.8 2968.85
   198.2 2968.56   220.5 2966.24   242.6 2966.98   252.22966.037   260.3 2964.75
   271.6 2966.07     286 2967.97   299.6 2966.29   322.4 2966.52   340.2 2965.81
   348.3 2966.59   363.1 2965.34   372.1 2966.14   405.2 2974.13   452.6  2978.3
     476 2987.68   480.9 2990.25   489.9 2996.45   496.9 2997.66   507.4 2998.09
#Mann= 4 ,-1,0
       0      .1       0   252.2    .045       0   271.6      .1       0
     450     .06       0
#XS Ineff= 2 , 0
           149.4 2970.69
Permanent Ineff=
       F       F
Bank Sta=252.2,271.6
XS Rating Curve= 0 ,0
Exp/Cntr(USF)=0,0
Exp/Cntr=0.3,0.1