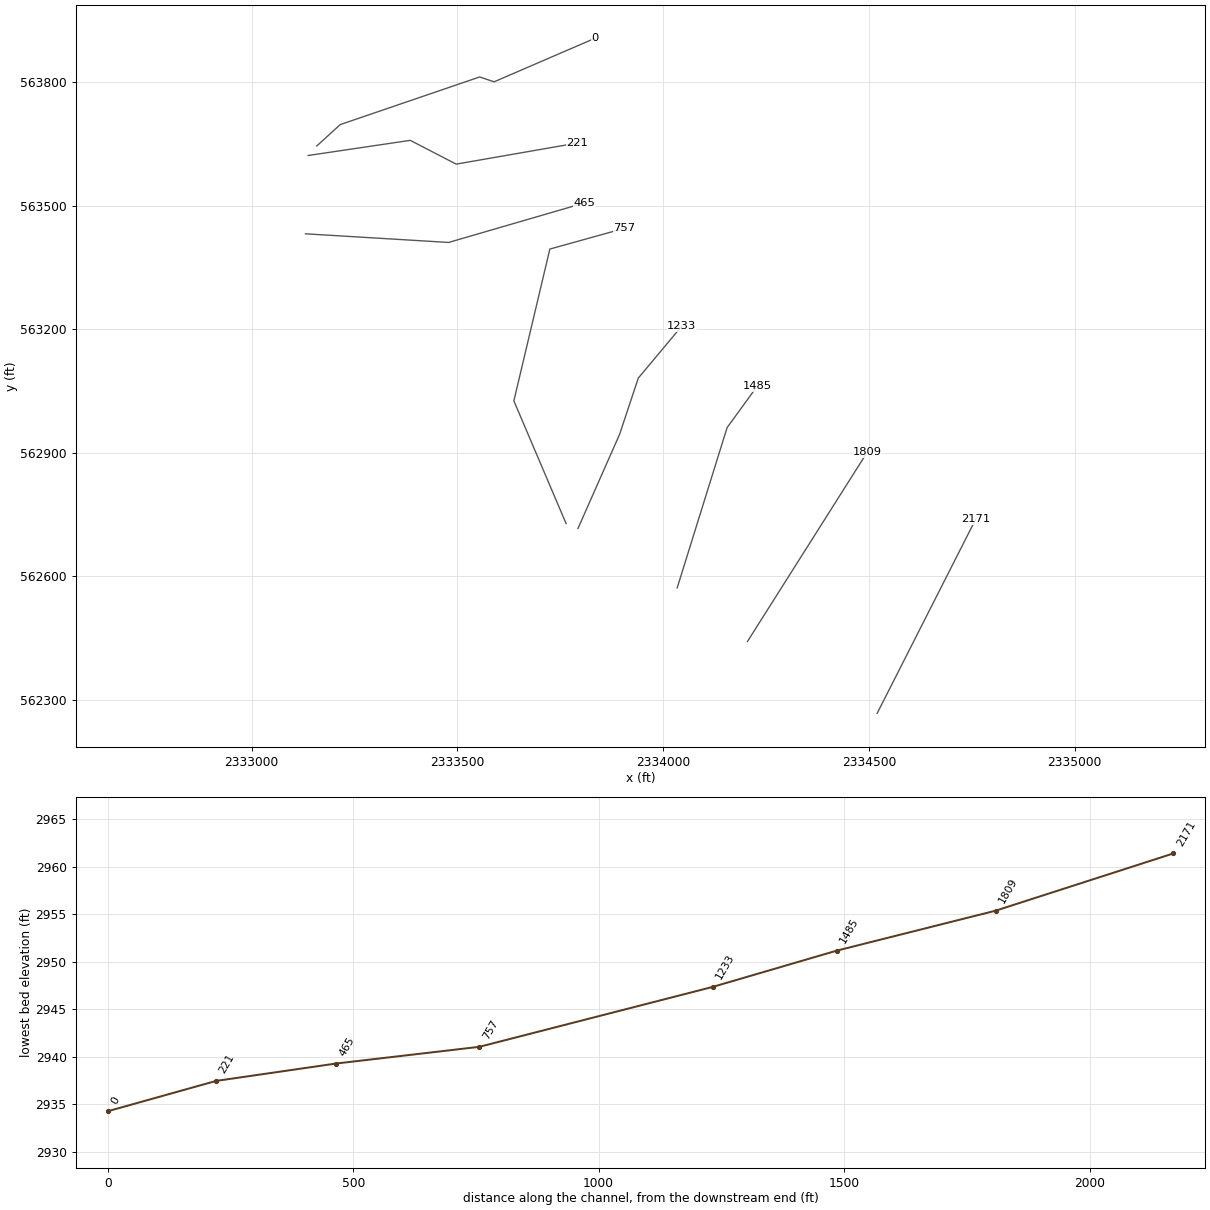
HEC-RAS study BFLFK.prj: BFLFK

--- BFLFK.g01 (geometry) --- (continued)

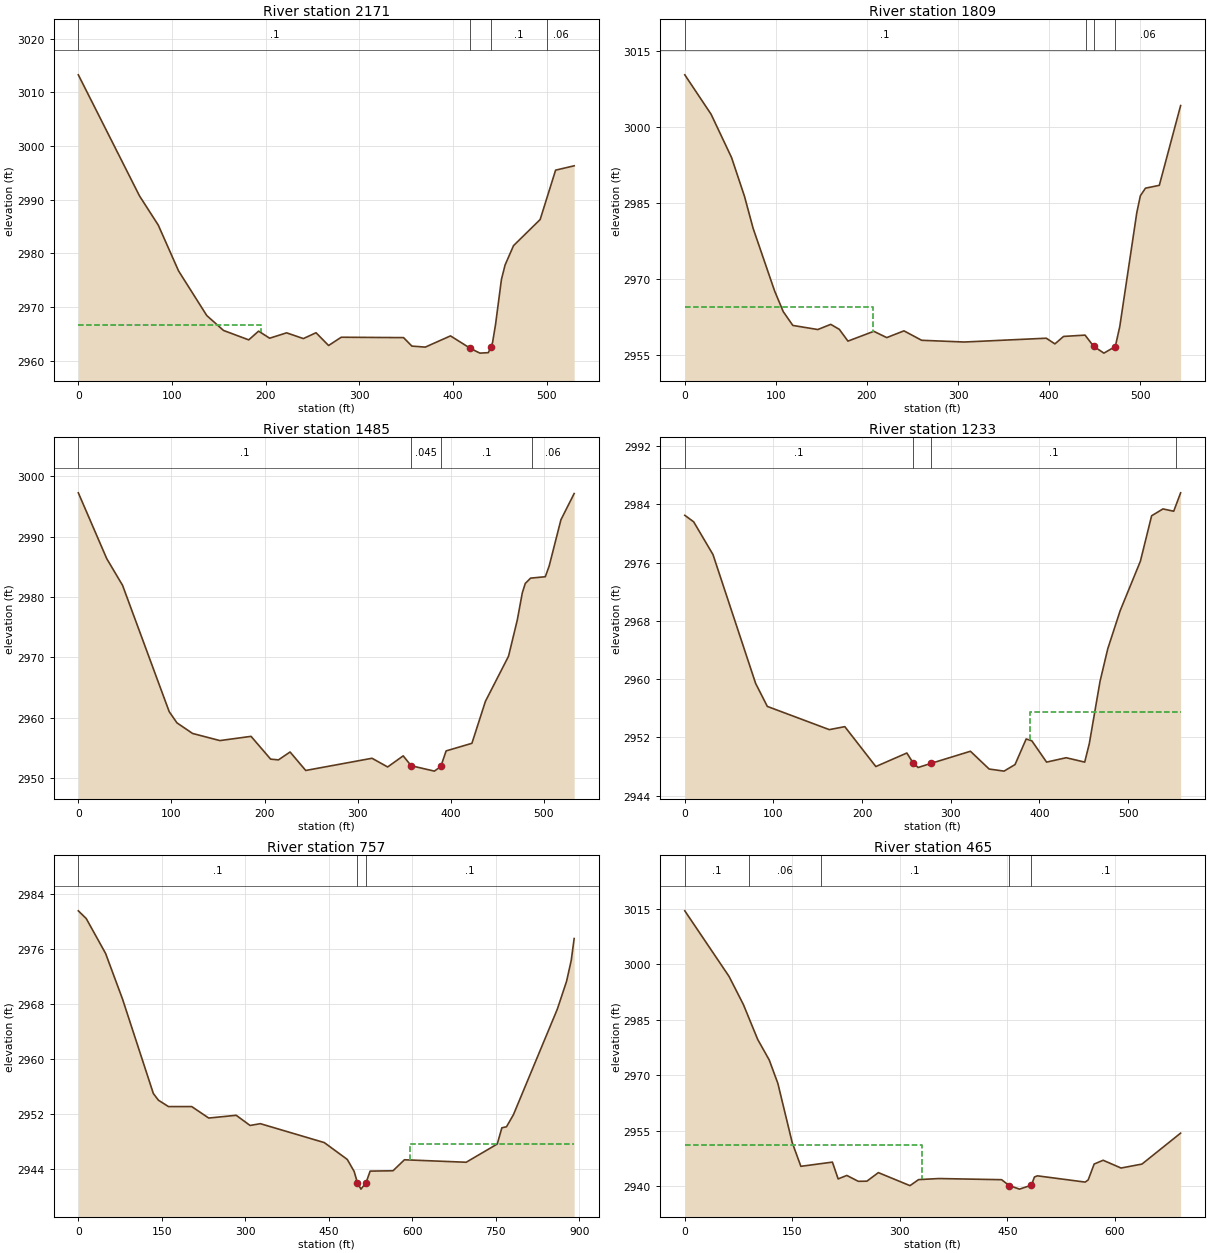
Type RM Length L Ch R = 1 ,2171    ,360.8,362.3,357.4
XS GIS Cut Line= 2
2334519.74350552 562266.968180422334759.29537228562738.885357937
#Sta/Elev= 30
       0 3013.26    65.3  2990.7    85.3 2985.27     107 2976.72   137.1 2968.41
     155 2965.63   181.9 2963.88   192.4 2965.51   204.2 2964.19   222.3 2965.19
   240.2 2964.12   253.7 2965.21   267.1 2962.83   280.6 2964.37   347.1  2964.3
     356 2962.72   370.3 2962.53   397.2 2964.62   418.5 2962.29   428.6 2961.41
   437.6  2961.5   440.32962.506   442.1 2963.37   445.3 2966.75   451.6 2975.16
   455.5 2977.84   464.5 2981.44   492.9  2986.3   509.4  2995.5   529.2 2996.31
#Mann= 4 ,-1,0
       0      .1       0   418.5    .045       0   440.3      .1       0
     500     .06       0
#XS Ineff= 2 , 0
          194.55 2966.57
Permanent Ineff=
       F       F
Bank Sta=418.5,440.3
XS Rating Curve= 0 ,0
Exp/Cntr(USF)=0,0
Exp/Cntr=0.3,0.1

Type RM Length L Ch R = 1 ,1809    ,319.3,323.9,328
XS GIS Cut Line= 2
2334204.73280073562441.8410431552334495.78831884562901.780627333
#Sta/Elev= 30
       0 3010.23    28.9 3002.45    51.3 2993.94    65.5  2986.3      75 2979.98
    98.6 2967.63   108.1 2963.55   118.6 2960.84     146 2960.03   160.2 2961.05
   169.6 2960.07   179.1 2957.75   207.5 2959.68   221.7 2958.44   240.6 2959.77
     260 2957.91   306.9 2957.57   396.8 2958.32   406.3  2957.2   415.8 2958.67
   439.4 2958.93   448.9 2956.71   460.1 2955.38   472.6 2956.68   477.5 2960.61
   496.2 2983.07   500.1 2986.39   505.7 2987.89   520.9 2988.45   544.3 3004.17
#Mann= 4 ,-1,0
       0      .1       0     440     .06       0   448.9    .045       0
   472.6     .06       0
#XS Ineff= 2 , 0
           206.2 2964.42
Permanent Ineff=
       F       F
Bank Sta=448.9,472.6
XS Rating Curve= 0 ,0
Exp/Cntr(USF)=0,0
Exp/Cntr=0.3,0.1

Type RM Length L Ch R = 1 ,1485    ,248.8,252.2,250.8
XS GIS Cut Line= 3
2334033.87243176562572.0374827392334155.12160912562961.285311036
 2334228.5203011563062.244445282
#Sta/Elev= 30
       0 2997.27    30.5 2986.37    47.5 2981.95    97.6 2961.02   105.9 2959.17
   122.7 2957.41     152 2956.23   185.5 2956.93   206.5 2953.16   214.9 2953.03
   227.4 2954.34   244.2 2951.28   315.4  2953.3   332.2 2951.86   348.9  2953.7
   357.4 2952.07   382.4 2951.17   389.3 2951.94     395 2954.52   422.7 2955.78
   437.2 2962.73     462  2970.2   471.4 2976.18   476.8 2980.69     480 2982.26
   485.7 2983.14   501.5 2983.37   505.7 2985.17   518.3 2992.81   532.5 2997.15
#Mann= 4 ,-1,0
       0      .1       0   357.4    .045       0   389.3      .1       0
   487.7     .06       0
Bank Sta=357.4,389.3
XS Rating Curve= 0 ,0
Exp/Cntr(USF)=0,0
Exp/Cntr=0.3,0.1

Type RM Length L Ch R = 1 ,1233    ,466,475.6,465.4
XS GIS Cut Line= 4
2333792.66744871562716.0578952112333894.11053048562945.532803097
2333939.33249942563081.6727855972334045.18356546563208.235565921
#Sta/Elev= 30
       0  2982.5      10 2981.61    31.8 2977.11    79.9 2959.41    93.1 2956.25
     163 2953.06   180.5 2953.47   215.5 2947.99   250.5 2949.85   257.4 2948.51
   263.2 2947.86   277.6 2948.42   322.2 2950.09   343.3 2947.65   360.1 2947.36
   372.5 2948.26   385.1 2951.78   391.5 2951.52   408.1  2948.6   430.2  2949.2
   451.1  2948.6   456.3 2951.14   468.4  2959.7   477.1 2964.16   491.1  2969.4
   513.9 2976.19   526.6 2982.44   539.4 2983.38   551.5 2983.06   559.3 2985.59
#Mann= 4 ,-1,0
       0      .1       0   257.4    .045       0   277.6      .1       0
  554.35     .06       0
#XS Ineff= 2 , 0
                          389.07         2955.52
Permanent Ineff=
       F       F
Bank Sta=257.4,277.6
XS Rating Curve= 0 ,0
Exp/Cntr(USF)=0,0
Exp/Cntr=0.3,0.1

Type RM Length L Ch R = 1 ,757     ,306.7,292,280.7
XS GIS Cut Line= 4
2333763.95736589562728.1055239322333636.99487651563026.347598048
2333724.43130788563395.2574728582333905.29296728563445.563364878
#Sta/Elev= 30
       0 2981.53    14.2 2980.41      49 2975.33    79.4  2968.7   134.8 2954.96
     144 2953.98     162 2953.06   203.7 2953.06   234.3 2951.39   283.7 2951.79
   308.6 2950.31   327.1 2950.57     442 2947.82   483.3 2945.37   495.6 2943.63
   501.5    2942   507.9 2941.05     5172941.994   524.4 2943.67   565.5 2943.72
     586 2945.32     697 2944.96   752.8 2947.61   761.1 2949.97   769.4 2950.12
   781.9 2951.88   860.8 2967.24   877.4 2971.29   885.7  2974.3     891  2977.5
#Mann= 3 ,-1,0
       0      .1       0   501.5    .045       0     517      .1       0
#XS Ineff= 2 , 0
                          595.78         2947.67
Permanent Ineff=
       F       F
Bank Sta=501.5,517
XS Rating Curve= 0 ,0
Exp/Cntr(USF)=0,0
Exp/Cntr=0.3,0.1

Type RM Length L Ch R = 1 ,465     ,255.2,244.3,232.1
XS GIS Cut Line= 3
2333130.61872401563432.3215751972333478.44345182563411.320836914
2333807.89253363563507.136705331
#Sta/Elev= 30
       0 3014.47    61.7 2996.76    81.7 2989.17   101.7 2979.73   117.8 2974.17
   129.8 2967.86   149.8 2951.88   161.9 2945.45   205.9 2946.59   213.9 2942.05
     226 2942.99     242  2941.4     254 2941.44     270 2943.75   314.1 2940.23
   326.1 2941.86   354.4 2942.15   441.9 2941.84   452.42940.265   466.9 2939.29
   483.4 2940.35   487.7 2942.57   491.9 2942.88   558.5 2941.19   562.7 2941.79
     571 2946.07   583.5 2947.09   608.5 2944.99   637.7 2946.06   691.6 2954.42
#Mann= 5 ,-1,0
       0      .1       0      90     .06       0     190      .1       0
   452.4    .045       0   483.4      .1       0
#XS Ineff= 2 , 0
          330.23 2951.13
Permanent Ineff=
       F       F
Bank Sta=452.4,483.4
XS Rating Curve= 0 ,0
Exp/Cntr=0.3,0.1

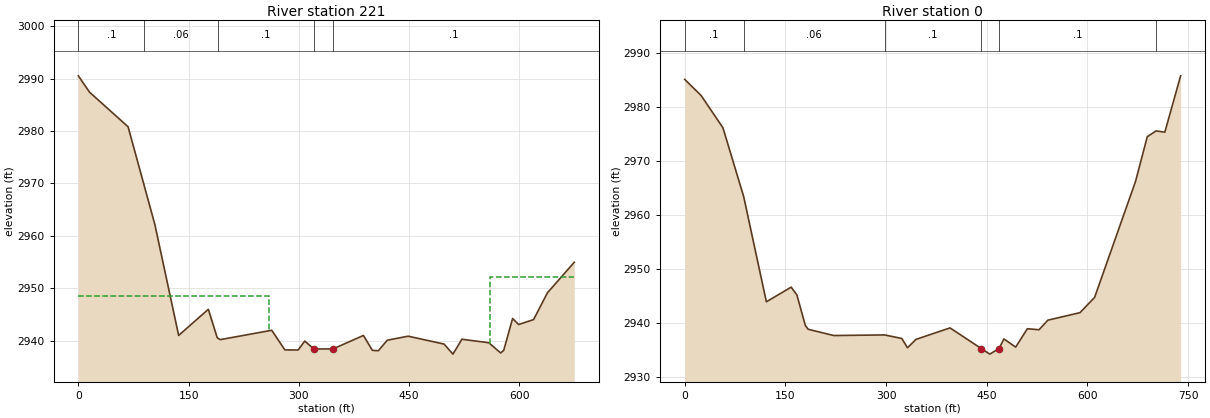
Type RM Length L Ch R = 1 ,221     ,215,220.6,229.6
XS GIS Cut Line= 4
2333137.18145472563622.6407658872333385.25267569563659.392057883
2333496.81909782563601.6400276042333790.82943378563652.829327169
#Sta/Elev= 30
       0 2990.53    15.2 2987.42    67.7 2980.81   104.1 2962.19   136.5 2941.03
   176.9 2946.01     189 2940.58   193.1 2940.22   263.1 2942.01   281.1 2938.26
   299.1 2938.25   308.1 2939.95   320.62938.431   346.6 2938.46   387.9 2941.02
   400.1 2938.18   408.2 2938.11   420.4 2940.12   448.8 2940.88   497.6 2939.38
   509.7 2937.46   521.9  2940.3   558.5 2939.63   574.7 2937.68   578.8 2938.19
   590.9 2944.25   599.1 2943.11   619.4 2944.04   638.3 2949.16   674.8 2954.98
#Mann= 5 ,-1,0
       0      .1       0      90     .06       0     190      .1       0
   320.6    .045       0   346.6      .1       0
#XS Ineff= 2 , 0
           259.3 2948.61  560.22         2952.17
Permanent Ineff=
       F       F
Bank Sta=320.6,346.6
XS Rating Curve= 0 ,0
Exp/Cntr=0.3,0.1

Type RM Length L Ch R = 1 ,0       ,91.6,107,118.6
XS GIS Cut Line= 5
2333158.06976182563645.7398800672333215.07748142563697.717506756
2333553.77040372563813.4096435812333588.98105405563801.672760135
2333833.77890878563907.304711148
#Sta/Elev= 30
       0  2985.1    24.5 2982.11      57 2976.14    87.9 2963.41   121.7 2943.95
   158.6 2946.66   167.1 2945.24   179.8 2939.56     184 2938.87     222 2937.71
     298 2937.82   323.5 2937.16   331.9 2935.45   344.6    2937   395.3 2939.12
   441.8 2935.31   454.5 2934.27   468.3 2935.31   475.6 2937.08   493.1 2935.57
   510.5 2938.97   527.9 2938.78     541 2940.55   588.9 2941.94   610.7 2944.77
   671.7 2966.24   689.1 2974.48   702.2 2975.56   715.3 2975.33   738.8 2985.75
#Mann= 6 ,-1,0
       0      .1       0    87.9     .06       0     298      .1       0
   441.8    .045       0   468.3      .1       0   702.2     .06       0
Bank Sta=441.8,468.3
XS Rating Curve= 0 ,0
Exp/Cntr=0.3,0.1
LCMann Table=0

Chan Stop Cuts=-1
Use User Specified Reach Order=0
Composite Channel Slope=5